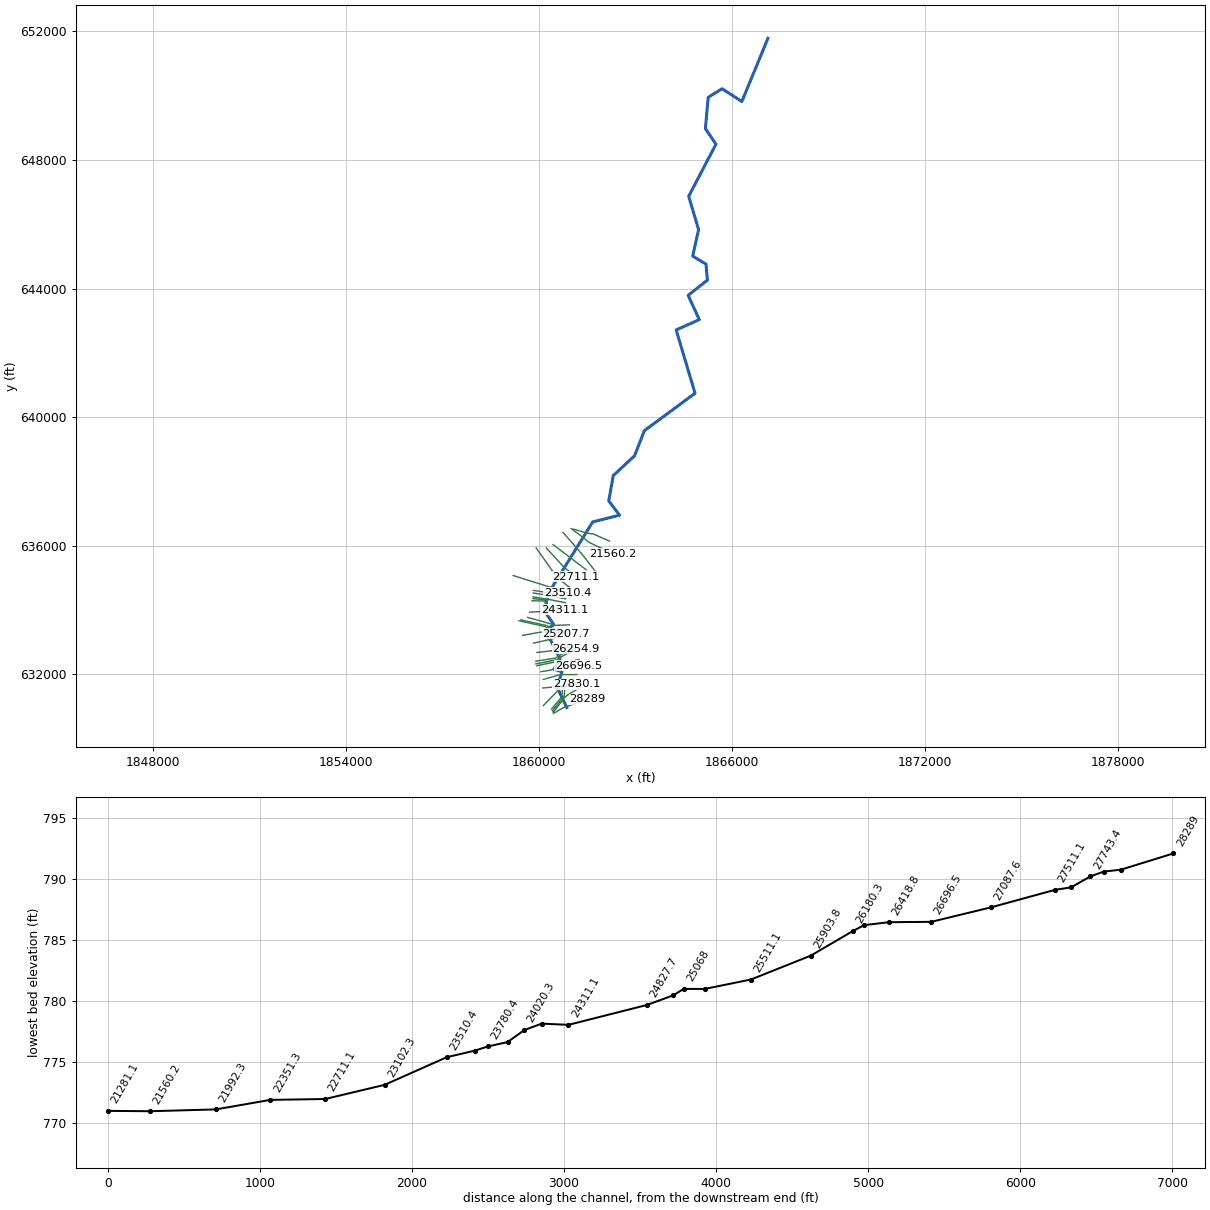
--- RFSpringCk.prj (project) ---

Proj Title=RFSpringCk
Current Plan=p01
Default Exp/Contr=0,0
English Units
Geom File=g01
Flow File=f01
Plan File=p01
BEGIN DESCRIPTION:
AMEC Environment & Infrastructure, 2013
Projection: NAD 1983 State Plane West Virginia South FIPS 4702 (US Feet)
Vertical Datum: NAVD 1988
END DESCRIPTION:
DSS Export Rating Curves= 0
DSS Export Rating Curve Sorted= 0
DSS Export Volume Flow Curves= 0
DXF OffsetX= 0
DXF OffsetY= 0
DXF ScaleX= 0
DXF ScaleY= 0

--- RFSpringCk.p01 (plan) ---

Plan Title=Floodplain
Program Version=4.00
Geom File=g01
Flow File=f01
K Sum by GR=0
Std Step Tol=0.01
Critical Tol=0.01
Num of Std Step Trials=20
Max Error Tol=0.3
Flow Tol Ratio=0.001
Split Flow NTrial=30
Split Flow Tol=0.02
Split Flow Ratio=0.02
Log Output Level=0
Friction Slope Method=1
Unsteady Friction Slope Method=2
Unsteady Bridges Friction Slope Method=1
Global Log Level=0
CheckData=False
Run HTab=0
Run UNet=0
Run PostProcess=0
UNET Theta=0
UNET Theta Warmup=0
UNET ZTol=0
UNET ZSATol=0
UNET MxIter=0
UNET MaxInSteps=0
UNET DtIC=0
UNET DtMin=0
UNET MaxCRTS=0
UNET WFStab=0
UNET SFStab=0
UNET WFX=0
UNET SFX=0
UNET DSS MLevel=0
UNET DZMax Abort=0
UNET Convert EG Bridges=0
UNET Use Existing IB Tables=0
UNET Froude Limit=0
UNET Froude Power=0
Write IC File=0
Echo Input=False
Echo Output=False
Write Detailed=0

--- RFSpringCk.f01 (steady flow) ---

Flow Title=NFF Regression Equation
Program Version=4.10
Number of Profiles= 1
Profile Names=P100yr
River Rch & RM=RFSpringCk,Main            ,28289
1308.305
River Rch & RM=RFSpringCk,Main            ,25207.7
1372.141
River Rch & RM=RFSpringCk,Main            ,24827.7
1484.049
River Rch & RM=RFSpringCk,Main            ,23510.4
1505.011
River Rch & RM=RFSpringCk,Main            ,23102.3
1989.166
River Rch & RM=RFSpringCk,Main            ,21992.3
2001.318
River Rch & RM=RFSpringCk,Main            ,21560.2
2130.766
River Rch & RM=RFSpringCk,Main            ,18244.2
2189.237
River Rch & RM=RFSpringCk,Main            ,17877.5
2252.696
River Rch & RM=RFSpringCk,Main            ,15541.4
2292.632
River Rch & RM=RFSpringCk,Main            ,15111.1
2388.252
River Rch & RM=RFSpringCk,Main            ,13217.7
2427.088
River Rch & RM=RFSpringCk,Main            ,12721.8
2500.245
River Rch & RM=RFSpringCk,Main            ,6141
2652.381
River Rch & RM=RFSpringCk,Main            ,5911.1
3792.639
River Rch & RM=RFSpringCk,Main            ,723.8
3841.475
River Rch & RM=RFSpringCk,Main            ,155.3
3865.045
Boundary for River Rch & Prof#=RFSpringCk,Main            , 1
Up Type= 0
Dn Type= 3
Dn Slope=0.0015
DSS Import GetInterval= 0
DSS Import GetPeak= 0
DSS Import FillOption= 0

--- RFSpringCk.g01 (geometry) ---

Geom Title=USGS 3m DEM
Program Version=4.10

River Reach=RFSpringCk      ,Main
Reach XY= 30
     1860860.213      630970.617     1860554.516      631607.983
     1860710.799      632083.856     1860457.232      632161.996
      1860651.73      632483.302     1860200.135      633369.014
     1860456.012      633547.481     1860181.001      633950.819
     1860269.547      634494.421      1861665.77      636743.566
     1862499.394      636952.017     1862163.206      637396.097
     1862303.081      638183.355     1862964.748       638799.93
     1863270.984      639581.911     1864845.542      640743.438
     1864258.306      642712.286     1864977.419       643034.21
     1864630.577       643788.28     1865228.814      644262.942
     1865185.741      644760.545     1864772.854      645008.797
       1864954.7      645833.843     1864648.111      646869.362
     1865494.692      648488.924     1865166.856      648977.368
     1865254.172      649947.164     1865685.646       650214.83
     1866300.005      649816.747     1867110.465      651781.378

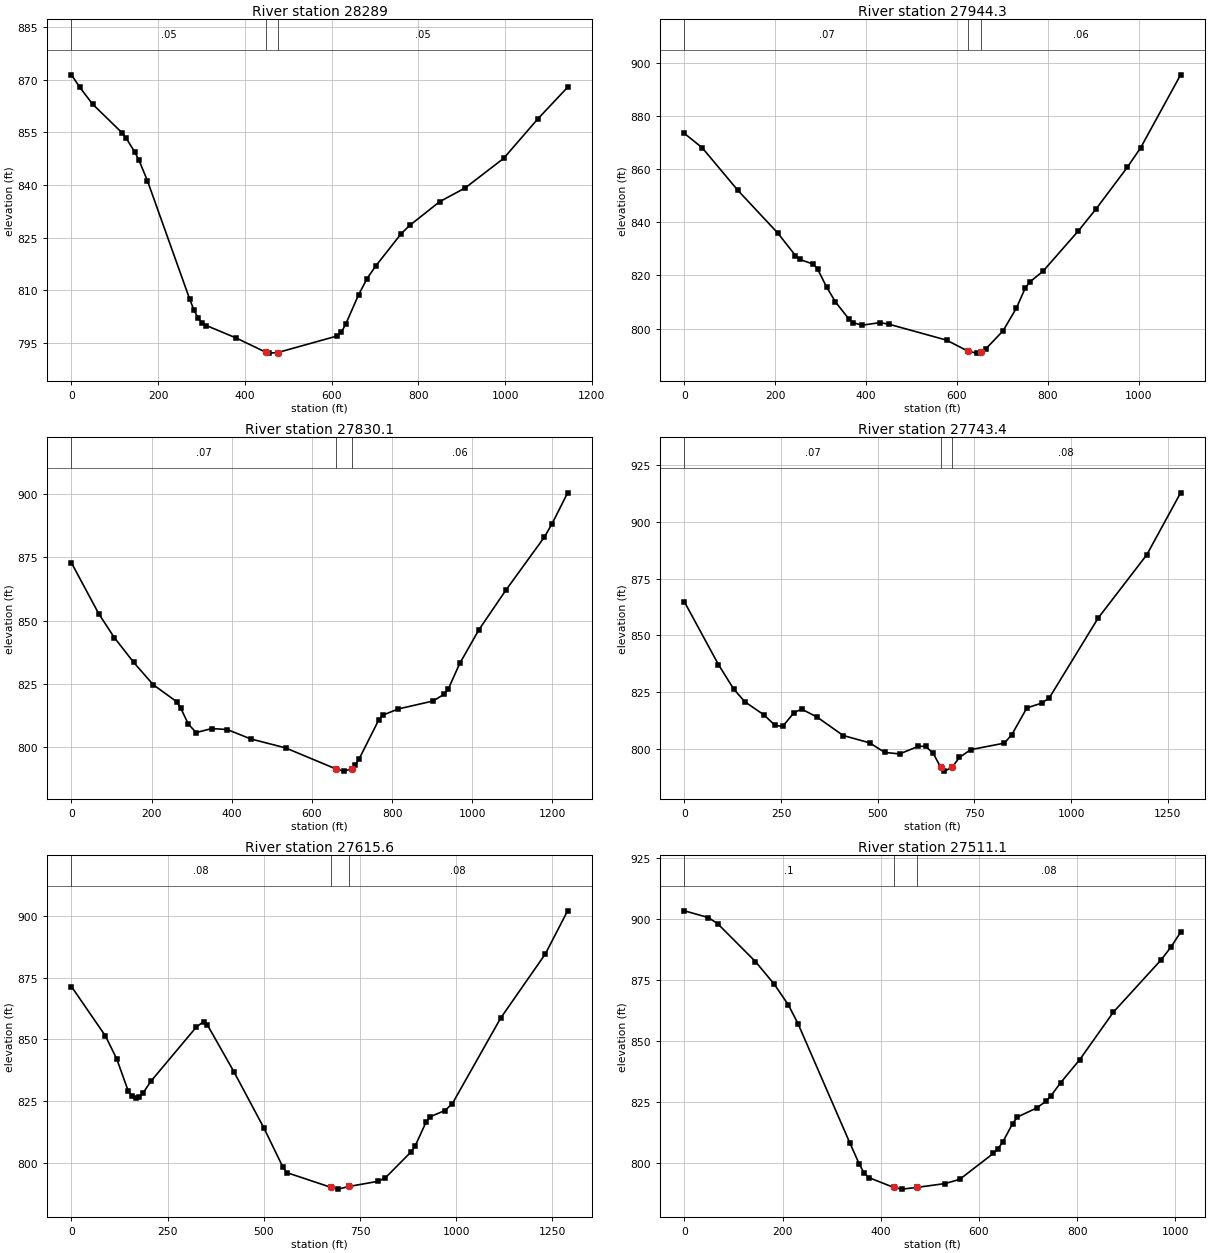
Type RM Length L Ch R = 1 ,28289   ,335.6,344.7,353.2
XS GIS Cut Line= 4
     1860444.485      630788.601     1860765.283      630972.002
     1860911.767      631021.916     1861499.094       631220.57
#Sta/Elev= 30
       0  871.44    19.4  867.84    48.6   863.1   116.7  854.91   126.4  853.33
   145.9  849.43   155.6  847.12     175  841.31   272.3  807.61     282  804.51
   291.7  802.16   301.4   800.7   311.2  799.96   379.2  796.45     448  792.37
   456.6   792.1   475.9  792.27   612.8  796.99   622.7  798.15   632.5  800.35
   662.1  808.72   681.7  813.34   701.4  816.89   760.5  826.16   780.2  828.52
     849  835.26   908.1   839.2   996.7  847.62  1075.4  858.85  1144.3   867.9
#Mann= 3 , 0 , 0
       0     .05       0     448    .045       0   475.9     .05       0
Bank Sta=448,475.9
XS Rating Curve= 0 ,0
Exp/Cntr=0.3,0.1

Type RM Length L Ch R = 1 ,27944.3 ,87.9,114.2,134.6
XS GIS Cut Line= 4
     1860436.507      630820.961     1860794.146      631286.239
     1860882.688      631359.155     1861218.599      631559.345
#Sta/Elev= 30
       0  873.39    39.1  868.02   117.4  852.04   205.4  835.95   244.5  827.46
   254.3  825.99   283.6  824.26   293.4  822.32     313  815.64   332.6     810
   361.9  803.66   371.7  802.22   391.2  801.28   430.4  802.24   449.9  801.67
   577.1  795.66   625.1  791.46   644.2  790.77   653.8  791.25   663.3  792.31
   701.6  799.16   730.9  807.68   750.4  815.21   760.2   817.5   789.5  821.55
   867.7   836.8   906.8  845.09   975.3  860.69  1004.6  868.02  1092.6  895.45
#Mann= 3 , 0 , 0
       0     .07       0   625.1    .045       0   653.8     .06       0
Bank Sta=625.1,653.8
XS Rating Curve= 0 ,0
Exp/Cntr=0.3,0.1

Type RM Length L Ch R = 1 ,27830.1 ,95.6,86.7,83.6
XS GIS Cut Line= 4
     1860410.465        630866.1     1860775.049      631320.961
     1860804.563      631609.155     1861160.465      631690.752
#Sta/Elev= 30
       0  872.76      68  852.71   106.9  843.29   155.4  833.46     204  824.69
   262.3  818.01     272  815.63   291.5  809.19   310.9  805.81   349.8   807.4
   388.6  807.02   446.9  803.33   534.4  799.76   660.2  791.45   679.5  790.61
   698.8  791.52   708.5  793.06   718.1  795.57   766.4  810.76   776.1  812.64
   814.7  815.11   901.5  818.25   930.3  820.97   939.9  822.96   968.7   833.1
  1016.8  846.46    1084  862.05  1180.1     883  1199.3  888.29  1237.8  900.39
#Mann= 3 , 0 , 0
       0     .07       0   660.2    .045       0   698.8     .06       0
Bank Sta=660.2,698.8
XS Rating Curve= 0 ,0
Exp/Cntr=0.3,0.1

Type RM Length L Ch R = 1 ,27743.4 ,140.8,127.8,115
XS GIS Cut Line= 4
     1860382.688      630921.655     1860693.451      631286.239
      1860738.59      631631.725     1861184.771      631725.475
#Sta/Elev= 30
       0  864.78      88  837.15   127.1  826.47   156.4  820.74   205.3  815.06
   234.6  810.34   254.2  809.94   283.5  816.02   303.1  817.53   342.2  814.14
   410.6  805.92   479.1  802.68   517.8  798.48   556.5   797.8   604.9  801.16
   624.2  801.15   643.6  798.01     663  791.86   672.6  790.22     692  791.84
   711.3  796.25   740.4  799.68   827.5  802.55   846.9  806.32   885.7  818.07
   924.5  820.22   943.9  822.53    1070  857.65  1196.1  885.61  1283.4  912.86
#Mann= 3 , 0 , 0
       0     .07       0     663    .045       0     692     .08       0
Bank Sta=663,692
XS Rating Curve= 0 ,0
Exp/Cntr=0.3,0.1

Type RM Length L Ch R = 1 ,27615.6 ,123.3,104.5,88.3
XS GIS Cut Line= 4
     1860130.517      631031.464     1860547.184      631461.152
     1860674.354      631625.214     1861145.708      631731.985
#Sta/Elev= 30
       0   871.4    88.3  851.37   117.7  842.06   147.2  829.19     157  827.08
   166.8   826.4   176.6   826.7   186.4  828.33     206  832.95   323.8  854.86
   343.4  857.23   353.2  855.86   421.9  836.95   500.4     814   549.5  798.22
   559.3  796.03     674  790.06   692.9  789.32   721.2   790.4   796.7  792.48
   815.8   793.9   883.4  804.54   893.1   806.8   922.1  816.67   931.8  818.64
   970.4  821.15   989.8  823.95  1115.4  858.62  1231.4  884.59  1289.4  902.08
#Mann= 3 , 0 , 0
       0     .08       0     674    .045       0   721.2     .08       0
Bank Sta=674,721.2
XS Rating Curve= 0 ,0
Exp/Cntr=0.3,0.1

Type RM Length L Ch R = 1 ,27511.1 ,423.3,423.5,420.4
XS GIS Cut Line= 3
     1860121.931      631578.749     1860553.604      631618.013
     1861118.995      631733.626
#Sta/Elev= 30
       0  903.35    48.2  900.61    67.4  898.12   144.5  882.54     183  873.21
   211.9  864.64   231.2  857.07   337.1  807.96   356.4  799.25     366  795.71
   375.7  793.85     426  789.82   443.2  789.12   472.6   789.8   531.3  791.42
   560.6  793.14   629.1  803.78   638.9  805.79   648.6  808.57   668.2  815.96
     678   818.7   717.1  822.41   736.7  825.24   746.4   827.4     766  832.76
   805.1  842.28   873.6  861.77   971.4  883.35     991  888.53  1010.5  894.56
#Mann= 3 , 0 , 0
       0      .1       0     426    .045       0   472.6     .08       0
Bank Sta=426,472.6
XS Rating Curve= 0 ,0
Exp/Cntr=0.3,0.1

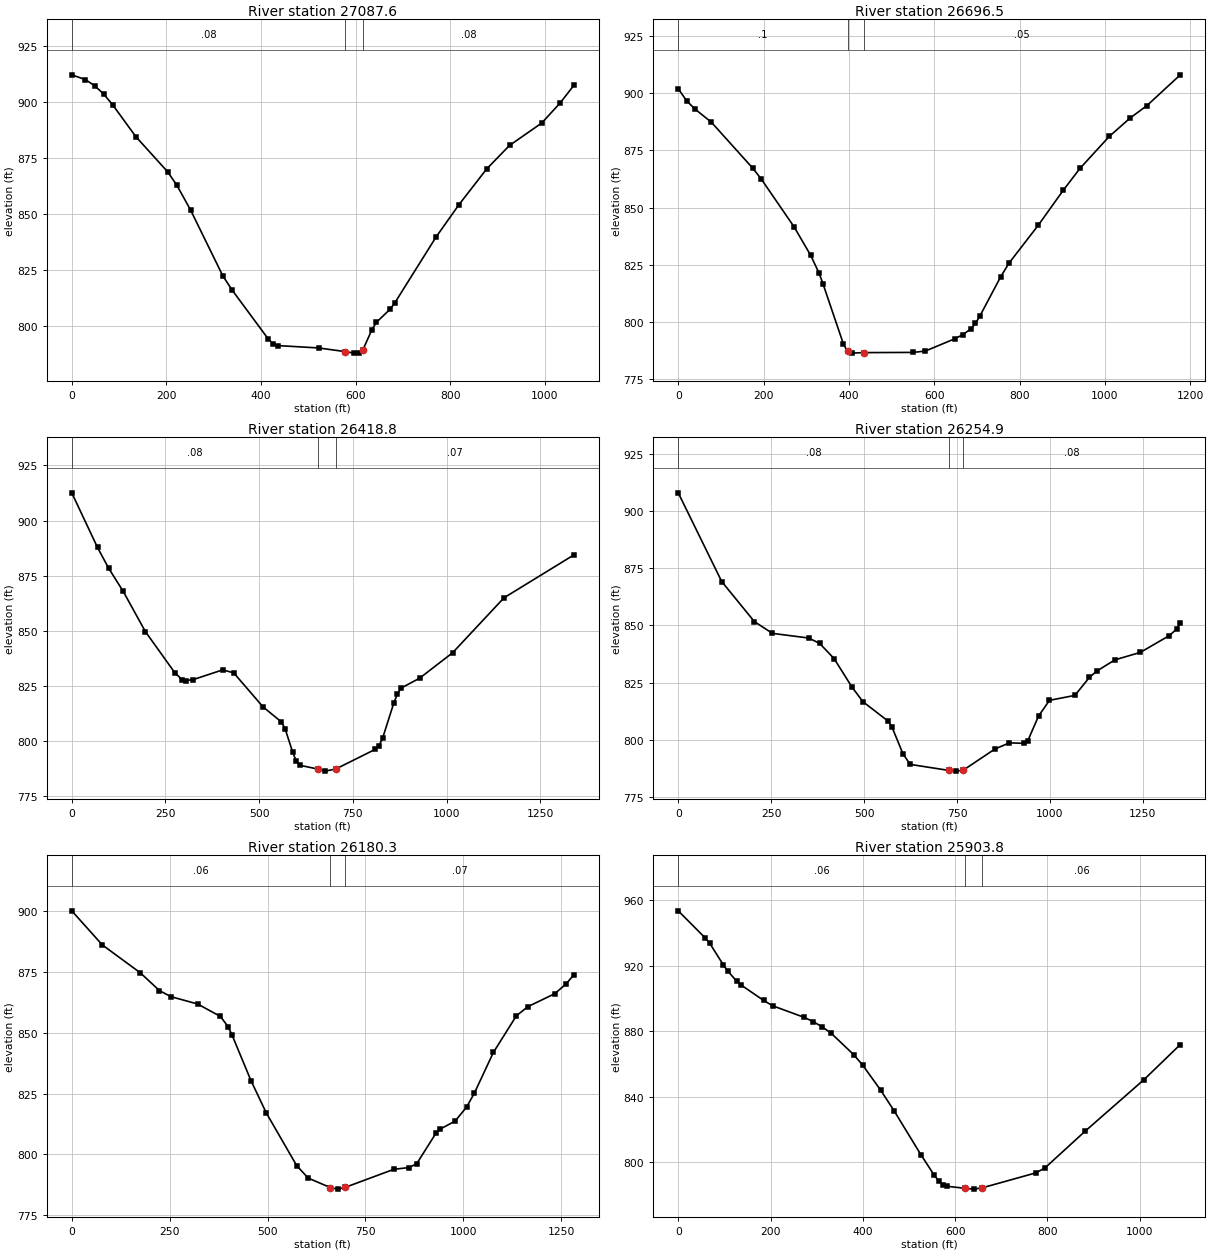
Type RM Length L Ch R = 1 ,27087.6 ,386.8,391,394.4
XS GIS Cut Line= 4
      1860127.31      631842.795     1860620.101      631982.419
     1860760.726      631992.836     1861168.712      631996.308
#Sta/Elev= 30
       0  912.31      29  910.16    48.3  907.43    67.6  903.68      87  898.73
   135.3  884.65   202.9  868.82   222.3   862.8   251.3  851.68   318.9  822.44
   338.2  816.14   415.6  793.92   425.2  791.88   434.9  791.07   521.6     790
     578  788.36   596.7  787.68   606.2  787.75   615.6  789.28   634.4  798.19
   643.8  801.45   672.6  807.31   682.3  810.04   769.8  839.63   818.3  854.14
   876.6  870.08   925.2  880.68   993.2  890.71  1032.1  899.67  1061.2  907.59
#Mann= 3 , 0 , 0
       0     .08       0     578    .045       0   615.6     .08       0
Bank Sta=578,615.6
XS Rating Curve= 0 ,0
Exp/Cntr=0.3,0.1

Type RM Length L Ch R = 1 ,26696.5 ,285.1,277.8,269.1
XS GIS Cut Line= 4
     1860057.601      632083.548     1860391.802      632142.141
     1860615.326      632196.395     1861218.625      632268.009
#Sta/Elev= 30
       0  901.81    19.4  896.61    38.8  892.99    77.6  887.21   174.5  867.18
   193.9  862.61   271.4   841.6   310.2  829.23   329.6  821.57   339.3  816.72
   387.2  790.46   396.8  787.26   406.4   786.5   435.1  786.73   550.2  786.81
   579.1   787.4   647.7  792.72   667.3  794.58   686.9  797.23   696.7  799.47
   706.5   802.5   755.5   819.7   775.1   825.7   843.7  842.22   902.5  857.54
   941.7  867.07  1010.3     881  1059.3  889.04  1098.5  894.43  1176.8  907.86
#Mann= 3 , 0 , 0
       0      .1       0   396.8    .045       0   435.1     .05       0
Bank Sta=396.8,435.1
XS Rating Curve= 0 ,0
Exp/Cntr=0.3,0.1

Type RM Length L Ch R = 1 ,26418.8 ,147,163.8,182.4
XS GIS Cut Line= 4
     1859926.715      632270.723     1860513.521      632390.515
     1860711.438      632352.321     1861239.215      632463.432
#Sta/Elev= 30
       0  912.59    68.7  887.82    98.2  878.47   137.4  867.89   196.4  849.71
   274.9  831.08   294.5  827.93   304.4  827.53     324  827.94   402.5  832.35
     432  831.03   510.5  815.56   559.6  808.74   569.4   805.6   589.1  795.28
   598.9     791   608.5  789.13   656.5  787.41   675.7  786.47   704.5  787.43
   810.3  796.38   820.1     798   829.9  801.64   859.3  817.32   869.1  821.45
   878.9  824.11     928  828.56  1016.2   840.1  1153.5  865.03  1339.8  884.44
#Mann= 3 , 0 , 0
       0     .08       0   656.5    .045       0   704.5     .07       0
Bank Sta=656.5,704.5
XS Rating Curve= 0 ,0
Exp/Cntr=0.3,0.1

Type RM Length L Ch R = 1 ,26254.9 ,75.4,74.6,72.2
XS GIS Cut Line= 4
     1859897.201      632326.279     1860556.924      632458.223
     1860688.868      632548.501     1861143.729      632796.765
#Sta/Elev= 30
       0  908.09     117  869.24   204.8  851.72   253.5  846.55     351  844.51
   380.3  842.18   419.3  835.52     468  822.89   497.3  816.58   565.5  808.02
   575.3  805.45   604.5  793.88     624  789.18   729.2  786.51     748  786.23
   766.8  786.63   852.2  795.93   891.3  798.61   930.4   798.4   940.2   799.4
   969.5  810.35   998.9  817.23  1067.3  819.39  1106.4   827.3    1126  830.01
  1174.9  834.95  1243.3  838.22  1321.5  845.59  1341.1  848.43  1350.9  851.13
#Mann= 3 , 0 , 0
       0     .08       0   729.2    .045       0   766.8     .08       0
Bank Sta=729.2,766.8
XS Rating Curve= 0 ,0
Exp/Cntr=0.3,0.1

Type RM Length L Ch R = 1 ,26180.3 ,284.1,276.5,269.1
XS GIS Cut Line= 4
     1859897.201      632411.348     1860503.104      632506.835
     1860648.938       632593.64     1861075.153      632853.189
#Sta/Elev= 30
       0  900.22    77.9  886.21   175.2   874.7   223.9  867.41   253.1  864.92
   321.3   861.9   379.7  856.77   399.2  852.56   408.9  849.27   457.6  830.39
   496.6  817.12   574.4   795.4   603.6   790.3   660.5  786.37   679.4  785.74
   698.2  786.46   822.2  793.88   861.4  794.63   880.9  796.21   929.9  808.73
   939.6  810.35   978.8   813.7  1008.1  819.48  1027.7   825.1  1076.6  841.96
  1135.4  857.05  1164.7   860.8  1233.2  866.12  1262.6  870.19  1282.1  873.92
#Mann= 3 , 0 , 0
       0     .06       0   660.5    .045       0   698.2     .07       0
Bank Sta=660.5,698.2
XS Rating Curve= 0 ,0
Exp/Cntr=0.3,0.1

Type RM Length L Ch R = 1 ,25903.8 ,390.6,392.7,394.9
XS GIS Cut Line= 4
     1859931.056       632683.05     1860473.135      632744.265
     1860641.125      632771.592     1860996.879      632880.886
#Sta/Elev= 30
       0  953.48    58.4  936.96    68.2  933.68    97.4  920.65   107.2   916.8
   126.6  910.54   136.4  908.19   185.1  898.81   204.6  895.56   272.8   888.5
   292.2  885.95   311.7  882.74   331.2  878.87   379.9  865.81   399.4  859.47
   438.4  844.17   467.6  831.58     526  804.62     555  792.11   564.4  788.71
   573.9   786.5   583.4  785.44   621.2  784.24   640.1  783.73     659  784.55
   774.5  793.61   794.1  796.53   882.2   819.2  1009.5  850.59  1087.9  871.92
#Mann= 3 , 0 , 0
       0     .06       0   621.2    .045       0     659     .06       0
Bank Sta=621.2,659
XS Rating Curve= 0 ,0
Exp/Cntr=0.3,0.1

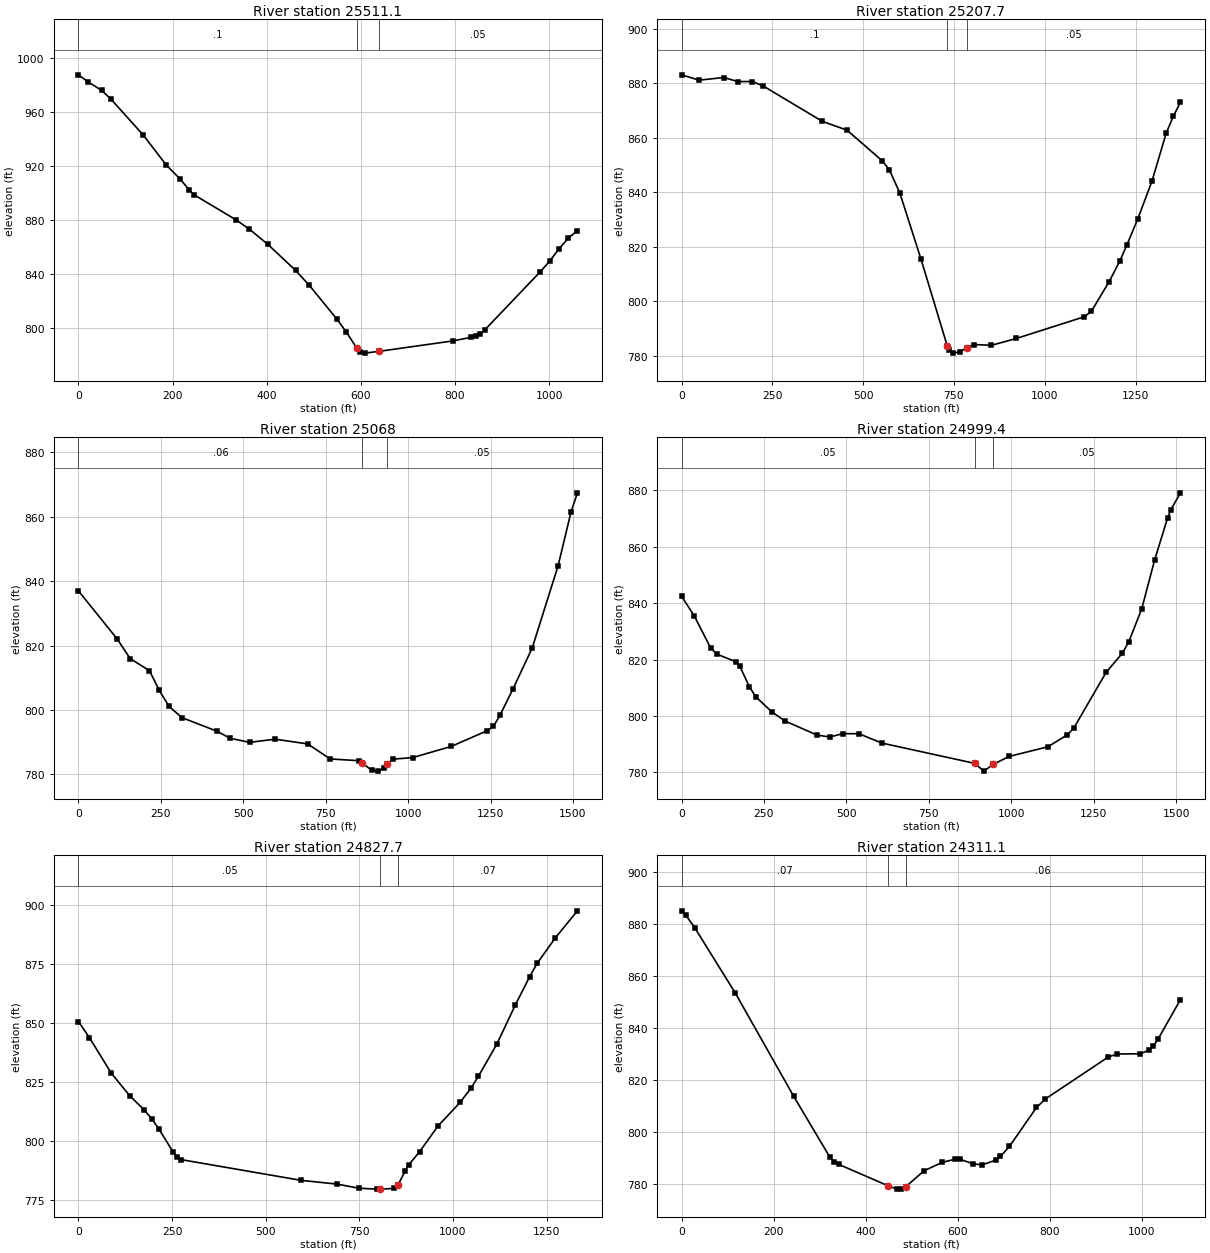
Type RM Length L Ch R = 1 ,25511.1 ,305.9,303.4,299.2
XS GIS Cut Line= 3
     1859822.115      632972.546     1860406.011       633103.87
     1860853.364      633217.704
#Sta/Elev= 30
       0  987.51    19.6  982.48    49.1  976.03    68.7  969.62   137.4  943.08
   186.4  920.85   215.8  910.55   235.5   902.3   245.3   898.9   333.6  880.53
     363  873.45   402.3  862.18   461.1  842.97   490.6  831.82   549.4  806.72
     569  797.41     591   785.6   598.5   782.8   608.3  781.78   637.8  783.07
   794.9  790.78   834.2  793.43     844  794.32   853.8  796.09   863.7  799.13
   981.5  842.07  1001.2  849.81  1020.8  858.82  1040.4  866.65  1060.1  872.41
#Mann= 3 , 0 , 0
       0      .1       0     591    .045       0   637.8     .05       0
Bank Sta=591,637.8
XS Rating Curve= 0 ,0
Exp/Cntr=0.3,0.1

Type RM Length L Ch R = 1 ,25207.7 ,158.2,139.7,122
XS GIS Cut Line= 4
     1859487.045      633213.866     1859973.156      633304.144
     1860309.962      633344.074     1860844.684      633267.685
#Sta/Elev= 30
       0  883.03    48.5  881.07   116.3  882.05   155.1  880.55   193.9  880.58
     223  879.08   387.8  865.97   455.6  862.75   552.6   851.5     572  848.27
     601  839.72   659.2  815.53   731.3   783.8   736.7     782   746.3  781.01
   765.8  781.45   785.1  782.94   804.5  784.17   853.2  783.87     922  786.39
  1108.6  794.32  1128.2  796.29  1177.3   807.2  1206.8  814.79  1226.4  820.72
  1255.9  830.13  1295.2  844.03  1334.4  861.66  1354.1  867.85  1373.7  872.98
#Mann= 3 , 0 , 0
       0      .1       0   731.3    .045       0   785.1     .05       0
Bank Sta=731.3,785.1
XS Rating Curve= 0 ,0
Exp/Cntr=0.3,0.1

Type RM Length L Ch R = 1 ,25068   ,69.8,68.6,67.3
XS GIS Cut Line= 4
     1859369.858      633669.595     1860201.455      633485.567
     1860274.372      633412.651     1860823.234      633308.481
#Sta/Elev= 30
       0  836.95   117.5  822.02   156.6  815.96   215.4  812.19   244.8  806.12
   274.1  801.19   313.3  797.64     421  793.36   460.1   791.2   518.9  789.95
   597.2  790.92   695.1  789.46   763.6  784.79   851.7  784.24   861.1  783.53
   889.2  781.25     908  781.01   926.7  781.85   936.1  783.26   954.8  784.74
  1013.6  785.21  1131.2   788.7  1239.1  793.53  1258.7   794.9  1278.3  798.31
  1317.5  806.42  1376.3  819.23  1454.7  844.71  1493.9  861.41  1513.5   867.4
#Mann= 3 , 0 , 0
       0     .06       0   861.1    .045       0   936.1     .05       0
Bank Sta=861.1,936.1
XS Rating Curve= 0 ,0
Exp/Cntr=0.3,0.1

Type RM Length L Ch R = 1 ,24999.4 ,161.2,171.8,182.1
XS GIS Cut Line= 4
     1859427.149      633697.373     1860258.747      633513.345
     1860331.663      633440.428     1860880.525      633336.259
#Sta/Elev= 30
       0  842.43    39.2  835.32    88.1  824.14   107.7  821.88   166.4  819.14
   176.2  817.78   205.6  810.42   225.2   806.8   274.1  801.44   313.3  798.27
   411.2  793.23   450.3  792.58   489.5  793.75   538.4  793.72     607  790.43
   889.2  783.23   917.3  780.48   945.5  782.88     994  785.69  1111.6  789.11
  1170.5  793.35  1190.1  795.75  1288.1  815.47  1337.1   822.2  1356.7  826.28
  1395.9  837.88  1435.1  855.22  1474.3  870.08  1484.1     873  1513.5  879.01
#Mann= 3 , 0 , 0
       0     .05       0   889.2    .045       0   945.5     .05       0
Bank Sta=889.2,945.5
XS Rating Curve= 0 ,0
Exp/Cntr=0.3,0.1

Type RM Length L Ch R = 1 ,24827.7 ,507.9,516.6,524.6
XS GIS Cut Line= 4
     1859643.295      633772.894     1860235.309      633609.699
     1860509.615       633524.63      1860940.17      633543.727
#Sta/Elev= 30
       0  850.72    29.2  843.94    87.7  828.82   136.5  819.36   175.5  813.23
     195  809.63   214.4  805.26   253.4  795.25   263.2  793.35   272.9  792.24
   594.6  783.42   690.7  781.83   748.1   780.1     796   779.7   805.6   779.7
   843.8     780   853.4  781.54   872.6  787.49   882.1  790.04   911.1  795.64
   960.1  806.48  1018.8  816.43  1048.2   822.5  1067.8  827.52  1116.8  841.11
  1165.8  857.56  1204.9  869.82  1224.5  875.37  1273.5  886.27  1332.3  897.68
#Mann= 3 , 0 , 0
       0     .05       0   805.6    .045       0   853.4     .07       0
Bank Sta=805.6,853.4
XS Rating Curve= 0 ,0
Exp/Cntr=0.3,0.1

Type RM Length L Ch R = 1 ,24311.1 ,232.2,176.2,87
XS GIS Cut Line= 3
     1859702.323      633936.088     1860179.503      633962.803
      1860783.92      634007.269
#Sta/Elev= 30
       0  885.14     9.8  883.36    29.3  878.48     117  853.47   243.8  813.76
   321.9  790.48   331.6  788.66   341.4   787.6   448.7  779.36   468.2  778.07
   477.9  778.14   487.7  779.08   526.8  785.11   565.9  788.34   595.2  789.64
     605  789.56   634.3  787.77   653.9  787.41   683.2  789.29     693  790.63
   712.5   794.5   771.2  809.48   790.7  812.78   927.6  828.95   947.1  830.05
     996  830.15  1015.6  831.48  1025.3  833.14  1035.1  835.72    1084  850.99
#Mann= 3 , 0 , 0
       0     .07       0   448.7    .045       0   487.7     .06       0
Bank Sta=448.7,487.7
XS Rating Curve= 0 ,0
Exp/Cntr=0.3,0.1

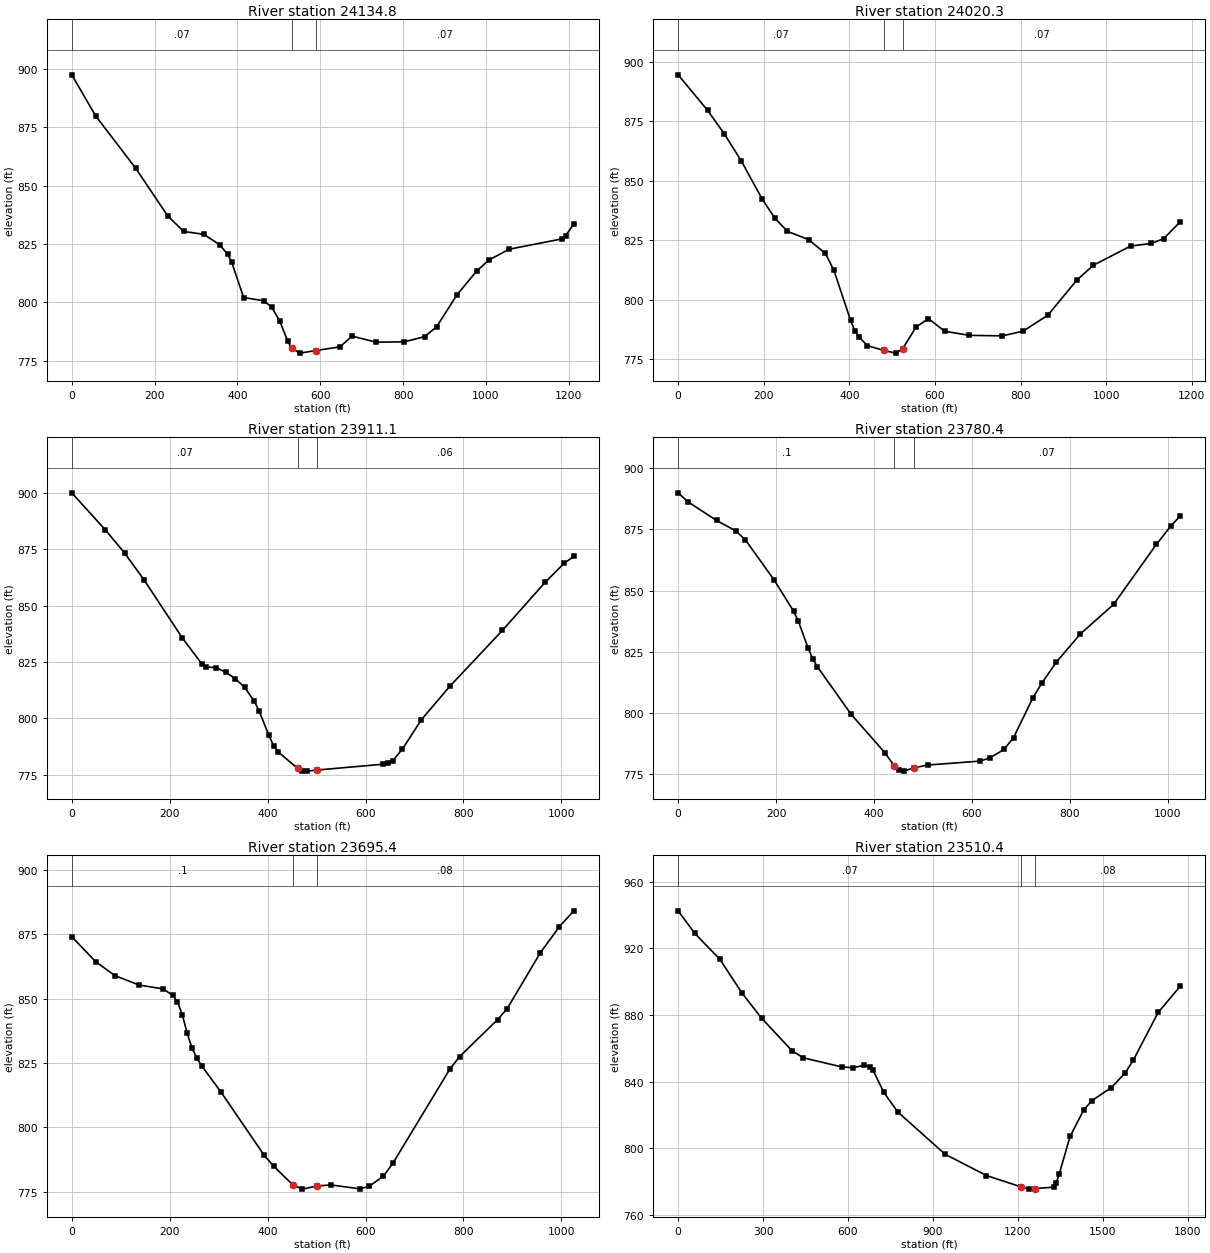
Type RM Length L Ch R = 1 ,24134.8 ,137.9,114.5,156
XS GIS Cut Line= 4
      1859775.24      634290.689      1860190.17      634283.744
      1860190.17      634051.105     1860754.406       634035.48
#Sta/Elev= 30
       0  897.57    57.9  879.89   154.4  857.47   231.6  837.05   270.2  830.38
   318.5  829.15   357.1  824.68   376.4  820.56     386  817.26     415  802.02
   463.5  800.64   482.8  797.87   502.2   791.9   521.6  783.23   531.3  780.19
   550.7  778.17   589.5  779.28   647.6  780.86   676.8  785.46   735.2  782.85
   803.3  783.04     852  785.25   881.2  789.51   929.8  803.14   978.5  813.54
  1007.7  818.18  1056.4  822.76  1182.9  827.16  1192.6  828.57  1212.1  833.63
#Mann= 3 , 0 , 0
       0     .07       0   531.3    .045       0   589.5     .07       0
Bank Sta=531.3,589.5
XS Rating Curve= 0 ,0
Exp/Cntr=0.3,0.1

Type RM Length L Ch R = 1 ,24020.3 ,33.8,109.3,150.5
XS GIS Cut Line= 4
     1859809.962      634358.397     1860249.198       634308.05
     1860250.934        634089.3     1860763.087      634078.883
#Sta/Elev= 30
       0  894.59    68.8  879.65   108.1  869.72   147.4  858.42   196.5  842.34
     226  834.34   255.4   828.8   304.6  825.37   343.9  819.56   363.5  812.63
   402.8   791.5   412.6  787.05   422.5  784.45   442.1  780.81   480.2  778.75
   508.7  777.64   524.3  779.43   556.2  788.64   584.8  792.13   622.8  786.85
   680.2   785.1   757.5   784.9   805.8  786.86   863.8  793.56   931.5   808.3
   970.2  814.56  1057.1  822.62  1105.5  823.74  1134.5  825.75  1173.1  832.78
#Mann= 3 , 0 , 0
       0     .07       0   480.2    .045       0   524.3     .07       0
Bank Sta=480.2,524.3
XS Rating Curve= 0 ,0
Exp/Cntr=0.3,0.1

Type RM Length L Ch R = 1 ,23911.1 ,130.7,130.7,131.2
XS GIS Cut Line= 3
     1859811.381      634411.226     1860286.226      634334.985
     1860820.378      634229.491
#Sta/Elev= 30
       0  899.91    68.7  883.48     108  873.23   147.2  861.49   225.7  835.71
     265  824.32   274.8  822.85   294.4  822.48   314.1  820.53   333.7  817.67
   353.3  813.72     373  807.57   382.8  803.25   402.4   792.6   412.2     788
     422  785.08   461.3  777.89   471.1   776.8   480.9  776.66   500.4  777.13
   636.5  779.73   646.2  780.12   655.9  781.35   675.4  786.42   714.3   799.5
   772.6  814.32   879.6  838.98   967.1  860.32    1006  868.77  1025.4  871.74
#Mann= 3 , 0 , 0
       0     .07       0   461.3    .045       0   500.4     .06       0
Bank Sta=461.3,500.4
XS Rating Curve= 0 ,0
Exp/Cntr=0.3,0.1

Type RM Length L Ch R = 1 ,23780.4 ,83.6,85,85.4
XS GIS Cut Line= 3
     1859814.853      634532.754     1860289.698      634456.513
     1860823.851      634351.019
#Sta/Elev= 30
       0  889.86    19.6  886.25    78.5  878.57   117.8  874.31   137.4  870.65
   196.3  854.22   235.6  841.61   245.4  837.54     265   826.7   274.8  822.13
   284.6  818.82   353.3  799.49     422  783.87   441.7  778.36   451.5  776.61
   461.3   776.3   480.9  777.64   510.1  778.79     617   780.4   636.5  781.69
   665.7  785.15   685.1     790     724  805.99   743.4  812.42   772.6  820.81
   821.2  832.22   889.3   844.3   976.8  868.83    1006  876.24  1025.4  880.39
#Mann= 3 , 0 , 0
       0      .1       0   441.7    .045       0   480.9     .07       0
Bank Sta=441.7,480.9
XS Rating Curve= 0 ,0
Exp/Cntr=0.3,0.1

Type RM Length L Ch R = 1 ,23695.4 ,189.7,185,180.6
XS GIS Cut Line= 3
     1859821.798      634614.351     1860296.642       634538.11
     1860830.795      634432.616
#Sta/Elev= 30
       0     874    49.1  864.27    88.3  858.89   137.4  855.24   186.5  853.74
   206.1  851.24   215.9  848.78   225.7  843.71   235.6  836.66   245.4   830.8
   255.2     827     265  823.94   304.3   813.8   392.6  789.22   412.2   784.9
   451.5  777.66   471.1  775.96   500.4  777.17   529.5  777.58   587.9  776.09
   607.3  777.04   636.5  780.99   655.9  786.01   772.6  822.67     792   827.4
   869.8   841.8   889.3  846.04   957.3  867.82   996.2  877.95  1025.4  884.06
#Mann= 3 , 0 , 0
       0      .1       0   451.5    .045       0   500.4     .08       0
Bank Sta=451.5,500.4
XS Rating Curve= 0 ,0
Exp/Cntr=0.3,0.1

Type RM Length L Ch R = 1 ,23510.4 ,417.2,408.1,398.4
XS GIS Cut Line= 4
     1859191.906      635075.411     1860213.157      634754.651
     1860455.795      634672.633     1860882.878      634539.821
#Sta/Elev= 30
       0  942.42    58.9  928.87   147.3  913.34   225.9  893.02   294.6  878.02
   402.6  858.41   441.9  854.23   579.4   848.7   618.7  848.31     658  849.75
   677.6  848.87   687.4  847.17   726.7  833.46   775.8  821.75   942.8   796.4
  1089.4  783.55  1212.7  776.72  1241.2  775.42  1260.2  775.76  1326.6  776.59
  1336.3  779.34    1346  784.24  1384.9  807.11  1433.5  823.09  1462.7   828.6
  1530.8  836.39  1579.4  845.14  1608.5  852.92    1696  881.44  1773.8  897.13
#Mann= 3 , 0 , 0
       0     .07       0  1212.7    .045       0  1260.2     .08       0
Bank Sta=1212.7,1260.2
XS Rating Curve= 0 ,0
Exp/Cntr=0.3,0.1

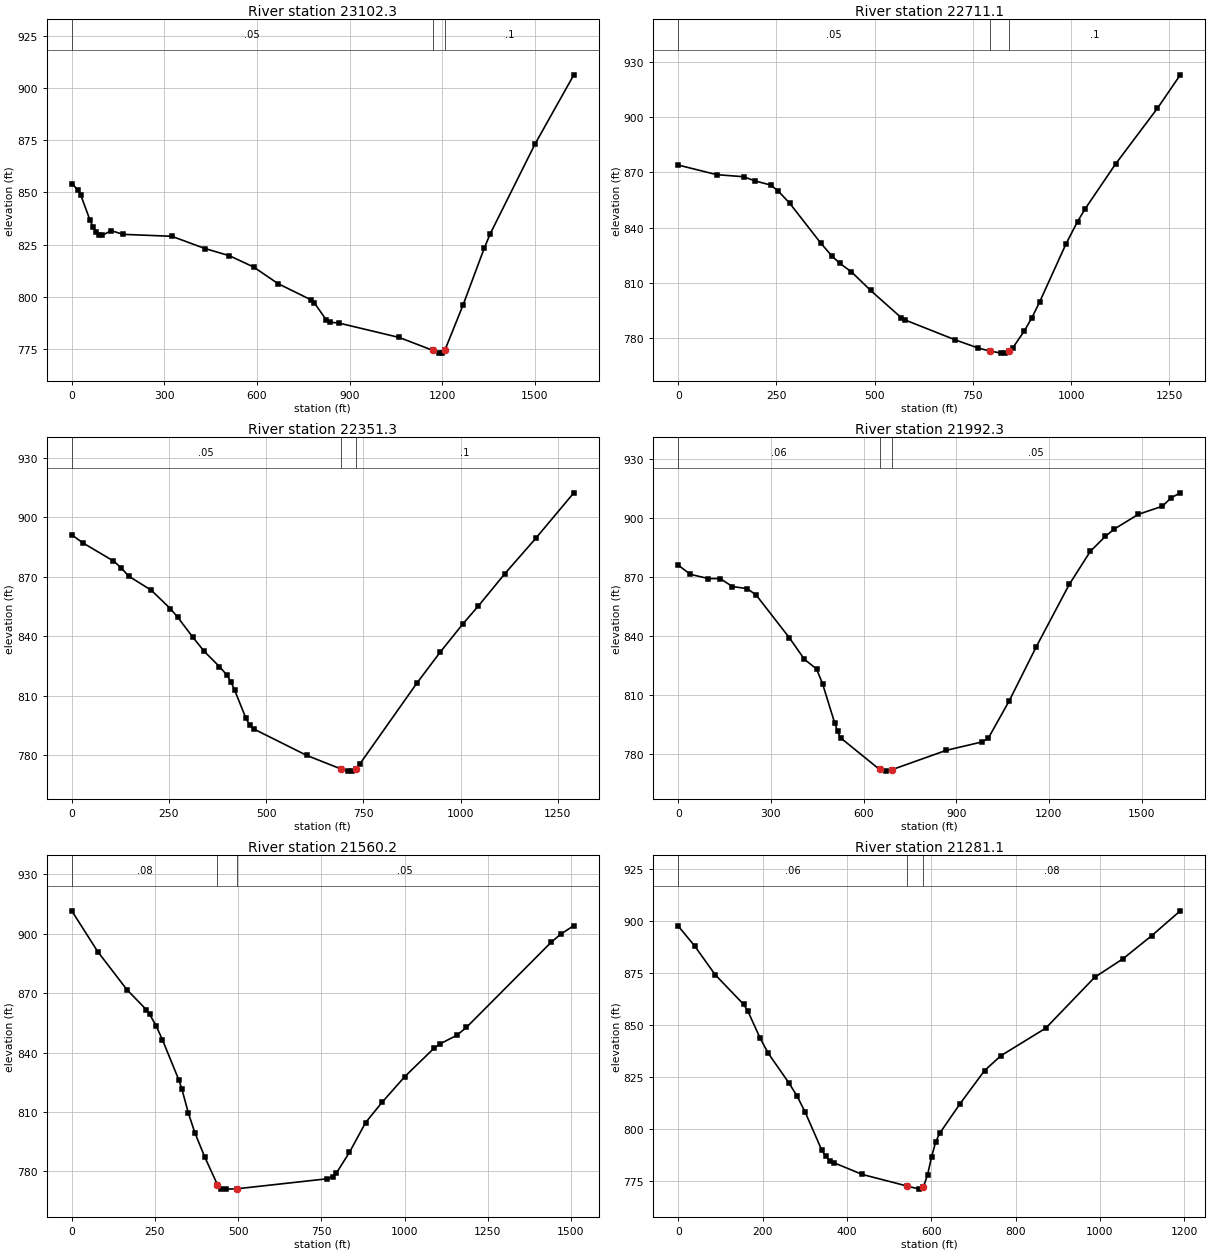
Type RM Length L Ch R = 1 ,23102.3 ,393.6,391.2,392.2
XS GIS Cut Line= 4
     1859907.184       635933.05     1860531.727      635050.966
      1860712.74      634884.439     1860952.323      634703.883
#Sta/Elev= 30
       0  854.22    19.6  851.28    29.5  848.61      59  836.78    68.8  833.48
    78.6  831.05    88.4  829.85    98.2  829.47   127.7  831.71     167  829.96
   324.2  829.03   432.3  823.15   510.9  819.74   589.5  814.32   668.1  806.41
   776.2  798.57     786  797.17   825.3  788.91   835.2  787.94   864.6  787.58
  1061.2  780.64  1169.3  774.51    1189  773.16  1198.9  773.19  1208.7  774.49
  1267.7  796.12  1336.4   823.3  1355.8  830.21    1501  873.14  1626.8  906.25
#Mann= 3 , 0 , 0
       0     .05       0  1169.3    .045       0  1208.7      .1       0
Bank Sta=1169.3,1208.7
XS Rating Curve= 0 ,0
Exp/Cntr=0.3,0.1

Type RM Length L Ch R = 1 ,22711.1 ,355.1,359.7,360.7
XS GIS Cut Line= 3
     1860223.156      635929.578     1860773.975      635331.747
     1861136.351      635040.689
#Sta/Elev= 30
       0  874.03    97.9  868.83   166.5   867.7   195.9   865.4     235  863.21
   254.6  859.93     284  853.22   362.4  831.78   391.8  824.52   411.4  820.68
   440.7  816.13   489.7  805.99     568  791.14   577.8  789.94   705.2  779.17
   763.9  774.73   793.3  773.12   822.6     772   832.3  772.08     842  772.93
   851.6  774.92   880.7  784.03     900  791.24   919.4  799.62   987.2  831.46
  1016.2  843.39  1035.6  850.32  1113.1  874.66  1219.6  904.86  1277.7  922.99
#Mann= 3 , 0 , 0
       0     .05       0   793.3    .045       0     842      .1       0
Bank Sta=793.3,842
XS Rating Curve= 0 ,0
Exp/Cntr=0.3,0.1

Type RM Length L Ch R = 1 ,22351.3 ,366.1,359.1,350.5
XS GIS Cut Line= 3
      1860431.49      636037.217      1860998.29      635608.243
     1861459.267      635255.967
#Sta/Elev= 30
       0  891.02    29.2  886.89   107.1  877.86   126.6  874.52   146.1  870.24
   204.5   863.1   253.2  853.89   272.6  849.45   311.6  839.34   340.8  832.25
   379.8   824.6   399.2  820.28     409  817.04   418.7  812.81   447.9  798.52
   457.7  795.16   467.4  793.23   603.7   779.9   691.4  773.08   710.8  771.93
   720.7  771.98   730.5  773.03   740.3  775.43   887.8   816.4   946.8  831.76
  1005.8  846.18  1045.2   855.1    1114  871.54  1192.7   889.2    1291  912.21
#Mann= 3 , 0 , 0
       0     .05       0   691.4    .045       0   730.5      .1       0
Bank Sta=691.4,730.5
XS Rating Curve= 0 ,0
Exp/Cntr=0.3,0.1

Type RM Length L Ch R = 1 ,21992.3 ,425.5,432.1,437.6
XS GIS Cut Line= 4
     1860740.517      636415.689     1861178.017      635919.161
     1861342.774      635725.151     1861778.712      635165.689
#Sta/Elev= 30
       0  876.03    38.9  871.37    97.3   869.2   136.2  869.18   175.2  865.13
   223.8  864.07     253  860.68   360.1  838.98   408.7  828.06   447.7  823.19
   467.1  815.74   506.1  795.89   515.8  791.36   525.5  788.11     652  771.98
   671.6  771.15   691.1  771.84   867.4  781.72   984.3  786.04  1003.8  787.88
  1071.8  806.99  1159.2  834.46  1266.1  866.22  1334.1  883.02  1382.7  890.64
  1411.8   894.4  1489.5  901.89  1567.3  906.01  1596.4  910.36  1625.6  912.85
#Mann= 3 , 0 , 0
       0     .06       0     652    .045       0   691.1     .05       0
Bank Sta=652,691.1
XS Rating Curve= 0 ,0
Exp/Cntr=0.3,0.1

Type RM Length L Ch R = 1 ,21560.2 ,266.3,279.1,291.6
XS GIS Cut Line= 4
     1860997.288      636535.046     1861316.733      636295.897
     1861540.257      636113.605     1862280.274      635757.703
#Sta/Elev= 30
       0  911.55    77.9  890.97   165.5  871.78   223.8  861.66   233.6  859.37
     253  853.62   272.5   846.4   321.2  826.34   330.9  821.51   350.4  809.38
   369.8  799.49     399  787.44   437.5  773.31   447.1  771.24   462.6     771
   495.2  771.16   765.7  776.19   785.2  777.27     795  779.07   834.1  789.52
     883  804.63   931.9  814.75  1000.3  827.77  1088.3  842.14  1107.8  844.46
  1156.7  848.67    1186   852.7  1440.2  895.64  1469.5  899.79  1508.6   904.1
#Mann= 3 , 0 , 0
       0     .08       0   437.5    .045       0   495.2     .05       0
Bank Sta=437.5,495.2
XS Rating Curve= 0 ,0
Exp/Cntr=0.3,0.1

Type RM Length L Ch R = 1 ,21281.1 ,98.6,113.1,128
XS GIS Cut Line= 4
      1861063.26      636519.421     1861511.177      636390.949
     1861683.052      636366.644      1862188.26      636146.158
#Sta/Elev= 30
       0  897.38    38.8  887.87    87.4  874.06   155.3  859.72     165  856.58
   194.2  843.57   213.6  836.24   262.1  822.16   281.5  815.84   300.9  808.07
   339.8  790.03   349.5  786.71   359.2  784.77   368.9  783.72   436.8  778.06
   543.1   772.5   572.1  771.03   581.7  772.23   591.3  777.88     601  786.66
   610.6  793.68   620.3   797.9   668.6  812.11   726.6  827.99   765.3  835.11
   871.7  848.35   987.7  872.78  1055.4  881.75  1123.1  892.79  1190.8   904.7
#Mann= 3 , 0 , 0
       0     .06       0   543.1    .045       0   581.7     .08       0
Bank Sta=543.1,581.7
XS Rating Curve= 0 ,0
Exp/Cntr=0.3,0.1