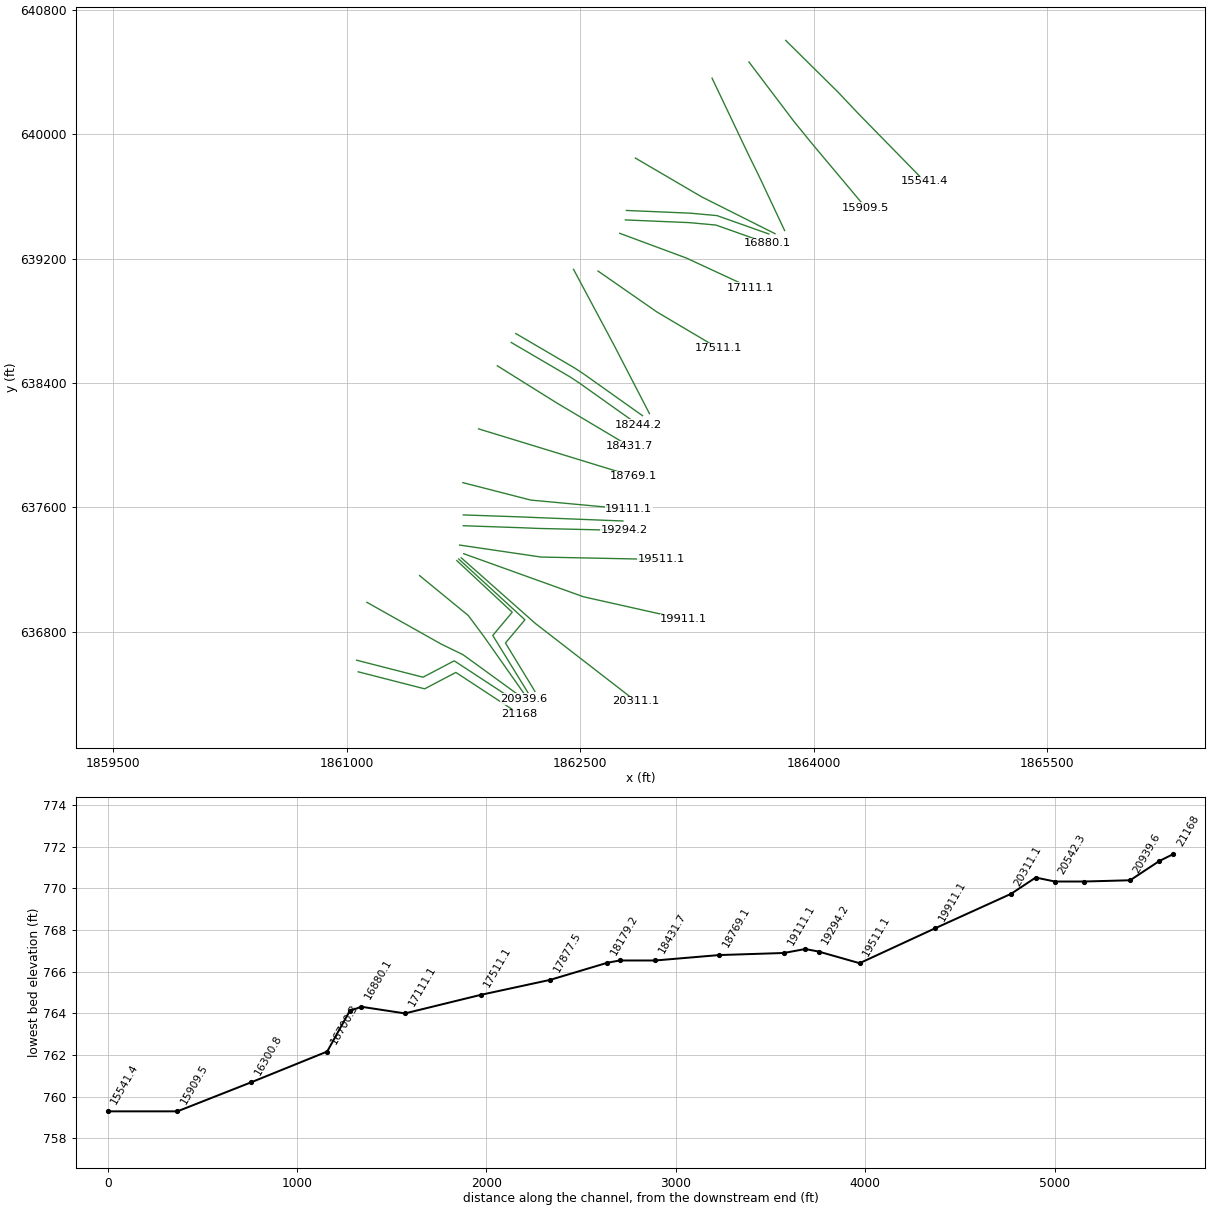
HEC-RAS study RFSpringCk.prj: RFSpringCk

--- RFSpringCk.g01 (geometry) --- (continued)

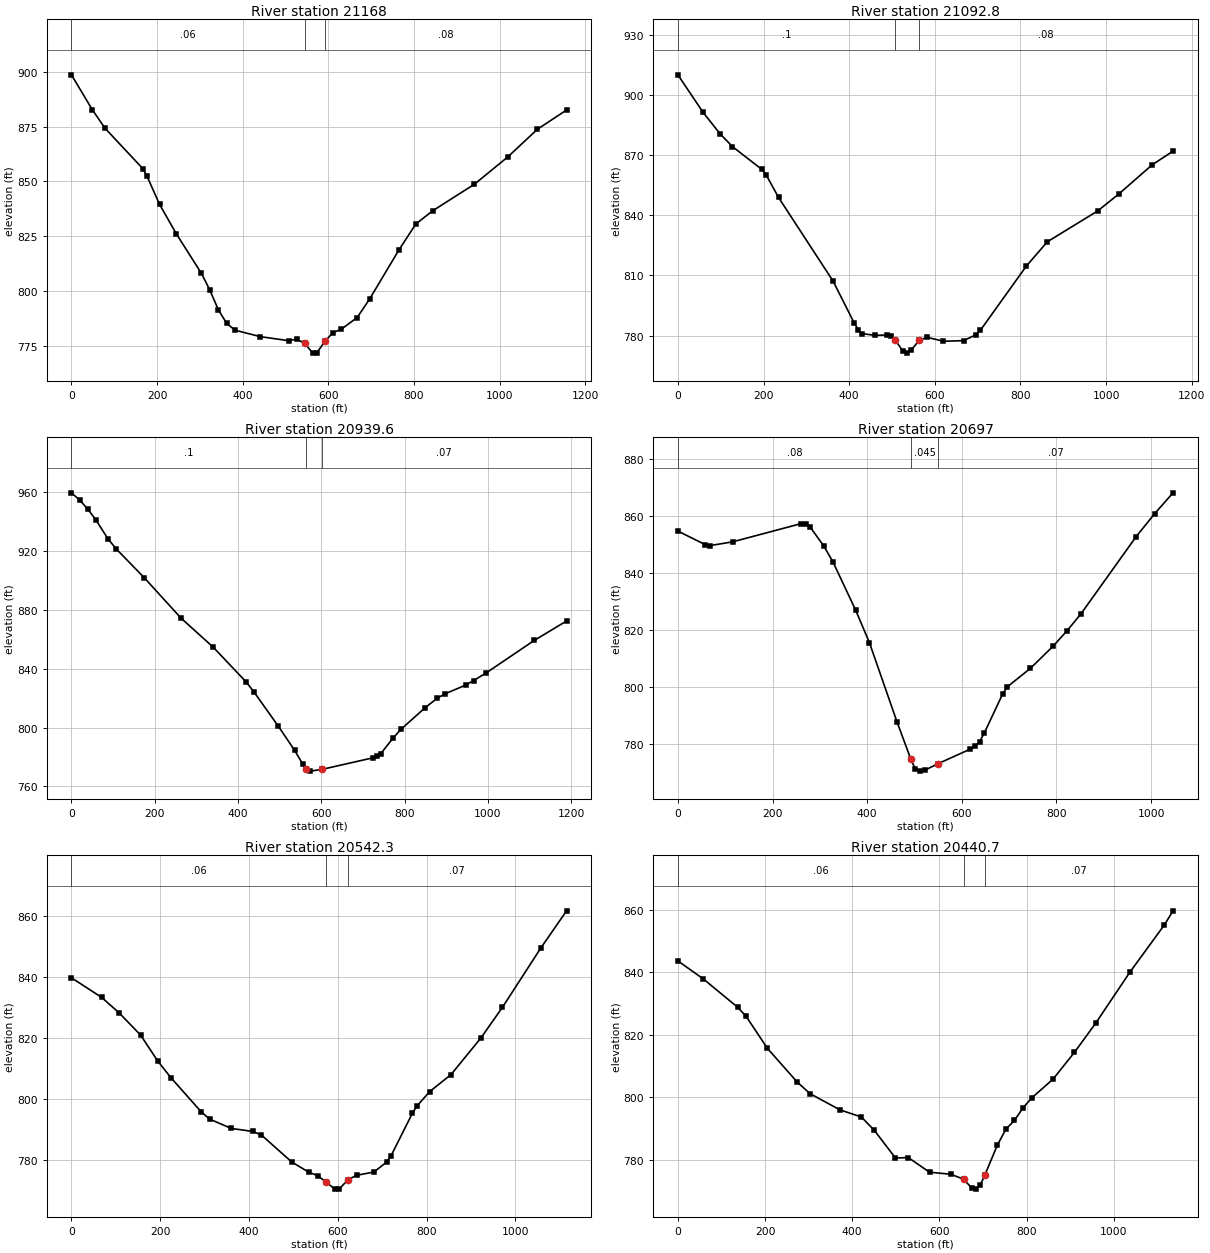
Type RM Length L Ch R = 1 ,21168   ,75.3,75.2,75.3
XS GIS Cut Line= 4
     1861073.243      636543.293     1861500.326      636433.918
     1861700.847      636539.387     1862109.701      636271.158
#Sta/Elev= 30
       0  898.61      49  882.63    78.4  874.26   166.6  855.83   176.4  852.44
   205.7  839.56   244.9  826.11   303.7     808   323.3  800.41   342.9  791.54
   362.5  785.21   382.1  782.12   440.9  779.18     507  777.33   525.8  778.02
   544.7  776.13   563.6  771.65     573   771.8   591.9  776.96   610.8  781.04
   629.7  782.47   667.4   787.9   696.8  796.46   765.2  818.84   804.4  830.56
   843.5  836.56   941.3  848.72  1019.5  861.22    1088  873.74  1156.4  882.57
#Mann= 3 , 0 , 0
       0     .06       0   544.7    .045       0   591.9     .08       0
Bank Sta=544.7,591.9
XS Rating Curve= 0 ,0
Exp/Cntr=0.3,0.1

Type RM Length L Ch R = 1 ,21092.8 ,174.4,153.3,130.8
XS GIS Cut Line= 4
     1861062.826      636617.946      1861489.91      636508.571
     1861690.431      636614.039     1862099.285       636345.81
#Sta/Elev= 30
       0  909.98    58.8  891.29      98  880.71   127.4  874.22   195.9  862.88
   205.7   860.3   235.1  848.86   362.5  807.16   411.5  786.44   421.3  782.89
   431.1  781.02   459.8  780.17   488.1  780.33   497.5  779.79     507  777.99
   525.8   772.2   535.3  771.31   544.7  772.66   563.6  777.78   582.5  779.17
   620.2  777.22   667.4  777.53   696.8  780.56   706.6  782.74   814.1  814.77
     863  826.82   980.4  842.16  1029.3  850.52  1107.5  865.12  1156.4  871.96
#Mann= 3 , 0 , 0
       0      .1       0     507    .045       0   563.6     .08       0
Bank Sta=507,563.6
XS Rating Curve= 0 ,0
Exp/Cntr=0.3,0.1

Type RM Length L Ch R = 1 ,20939.6 ,253.1,242.6,232.1
XS GIS Cut Line= 4
     1861129.233      636989.908     1861604.927      636722.546
     1861747.288      636653.102     1862139.649       636368.38
#Sta/Elev= 30
       0  959.77    19.5  954.94      39  948.77    58.5  941.43    87.7  928.49
   107.2  921.71   175.4  901.84   263.1  874.53     341  854.58     419  831.23
   438.5   824.2     497  800.87   535.9  784.53     555  775.31   564.3  771.86
   573.6  770.39   601.6  771.58   723.5  779.42   733.2  780.45   742.9  782.32
     772  792.78   791.3  798.85   849.5   813.6   878.6  820.05     898   823.1
   946.5  828.94   965.9  832.04     995  837.06  1111.3  859.34  1188.9  872.55
#Mann= 3 , 0 , 0
       0      .1       0   564.3    .045       0   601.6     .07       0
Bank Sta=564.3,601.6
XS Rating Curve= 0 ,0
Exp/Cntr=0.3,0.1

Type RM Length L Ch R = 1 ,20697   ,186.5,154.7,121.1
XS GIS Cut Line= 4
     1861467.774      637161.783     1861780.803      636905.135
     1861879.233      636772.894      1862153.43       636382.92
#Sta/Elev= 30
       0  854.75    57.8  849.99    67.5  849.64   115.6  850.97   260.2  857.37
   269.9  857.25   279.5  856.18   308.4  849.48   327.7  843.92   375.9  826.86
   404.8   815.5     463  787.67   492.1   774.6   501.8  771.01   511.5  770.33
   521.2   770.6   550.2  772.98   618.3   778.1     628     779   637.8  780.75
   647.5  783.71   686.4   797.5   696.1  799.97   744.8  806.45   793.4  814.36
   822.6  819.74   851.8  825.65   968.5  852.82  1007.4  860.86  1046.4  868.21
#Mann= 3 , 0 , 0
       0     .08       0   492.1    .045       0   550.2     .07       0
Bank Sta=492.1,550.2
XS Rating Curve= 0 ,0
Exp/Cntr=0.3,0.1

Type RM Length L Ch R = 1 ,20542.3 ,101.6,101.6,103.2
XS GIS Cut Line= 4
     1861707.249       637257.92     1862063.152      636926.322
     1861938.152      636777.017     1862165.582      636407.225
#Sta/Elev= 30
       0  839.66    68.1  833.22     107  828.21   155.7  820.88   194.6  812.32
   223.8  806.93   291.9  795.76   311.3   793.3     360  790.24   408.6  789.25
   428.1  788.06   496.2  779.24   535.1  775.84   554.6  774.77   574.1  772.59
   593.5  770.33   603.3  770.38   622.8   773.4   642.2  774.86   681.2  775.94
   710.1  779.21   719.8  781.22     768  795.23   777.6  797.47   806.6  802.28
   854.8  807.87   922.4  819.93   970.6  829.92  1057.4  849.45  1115.3  861.62
#Mann= 3 , 0 , 0
       0     .06       0   574.1    .045       0   622.8     .07       0
Bank Sta=574.1,622.8
XS Rating Curve= 0 ,0
Exp/Cntr=0.3,0.1

Type RM Length L Ch R = 1 ,20440.7 ,93.1,129.6,167.5
XS GIS Cut Line= 4
     1861719.402      637268.336     1862144.749      636877.711
     1862019.749      636728.406     1862208.985      636417.642
#Sta/Elev= 30
       0  843.64    58.7  837.82     137   828.8   156.6  825.86   205.6  815.58
   274.1  804.77   303.4  801.09     372   795.9   420.9  793.64   450.3  789.42
   499.2  780.49   528.6  780.63   577.5  775.94   626.2  775.29   655.4   773.7
   674.9  770.78   684.6  770.52   694.3  771.98   704.1  774.98   733.3  784.71
   752.8  789.77   772.2  792.54   791.9  796.55   811.6  799.72   860.7  805.74
   909.9  814.34   959.1  823.78  1037.7  840.15  1116.4  855.21  1136.1  859.68
#Mann= 3 , 0 , 0
       0     .06       0   655.4    .045       0   704.1     .07       0
Bank Sta=655.4,704.1
XS Rating Curve= 0 ,0
Exp/Cntr=0.3,0.1

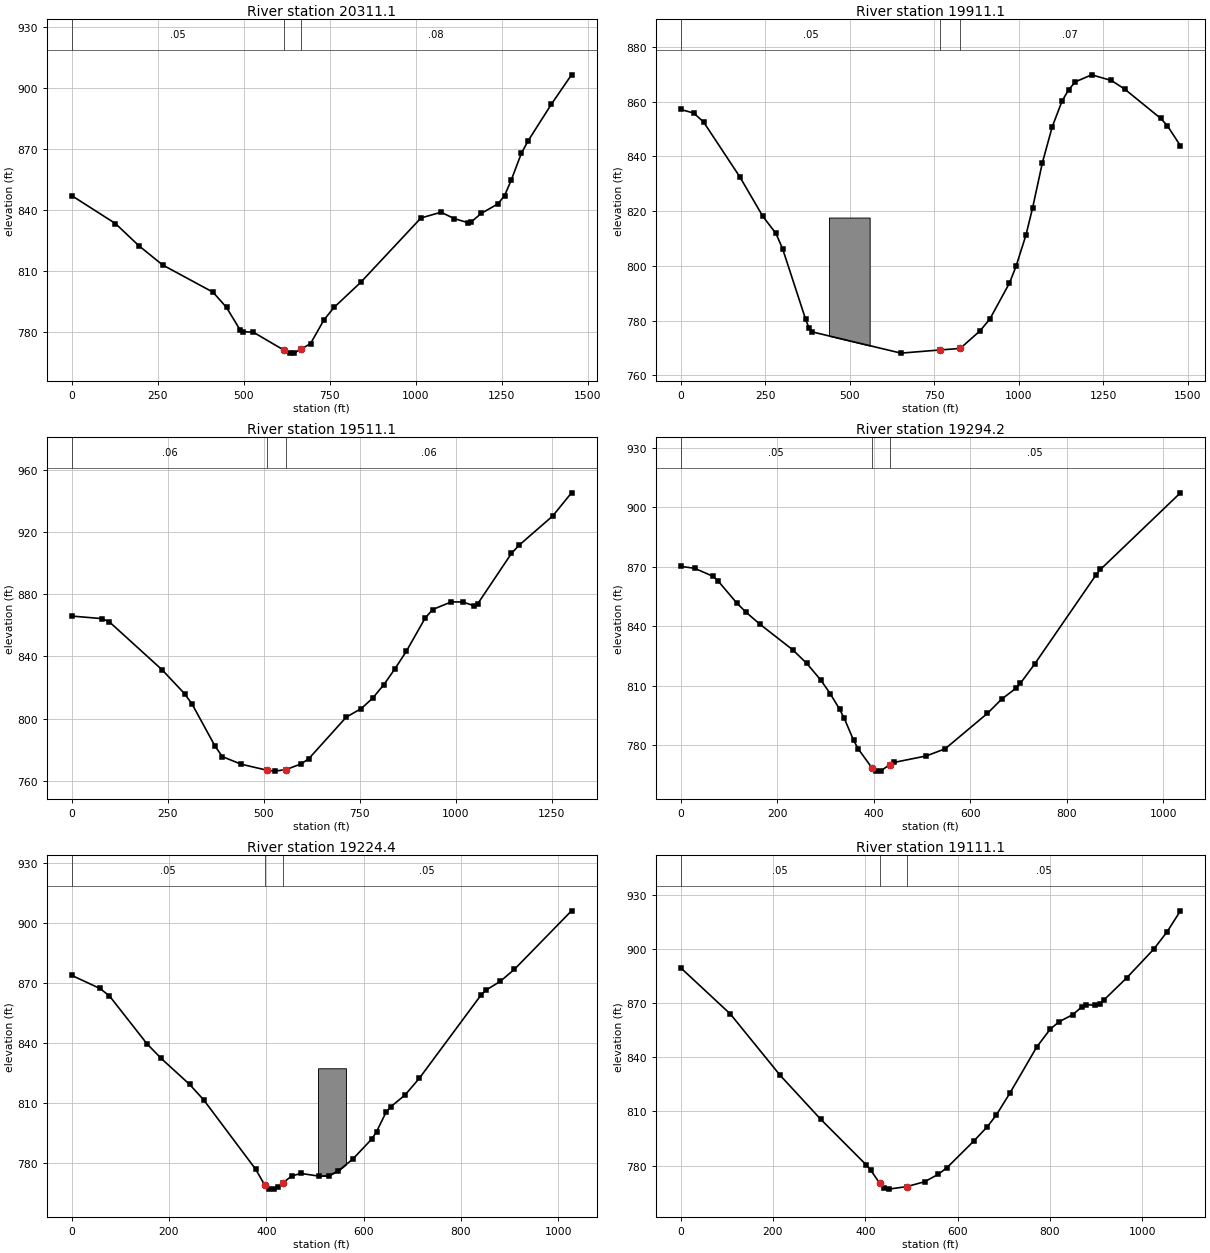
Type RM Length L Ch R = 1 ,20311.1 ,390.8,400,410.1
XS GIS Cut Line= 3
     1861735.569      637276.149     1862211.663      636854.276
     1862857.857      636354.274
#Sta/Elev= 30
       0  847.24   127.2  833.48   195.7  822.52   264.2  813.13     411  799.71
   450.2  792.21   489.3  781.26   499.1  780.32   528.5  779.99   616.5  771.27
   636.1  769.74   645.8  769.74   665.3  771.53   694.5  774.43   733.4  786.07
   762.6  792.19   840.4  804.57  1015.5  836.22  1073.8  839.04  1112.7  835.88
  1151.6  833.94  1161.4  834.26  1190.5  838.44  1239.2  843.14  1258.6  847.24
  1278.1  854.92  1307.3  867.98  1326.7  874.08  1394.8  892.21  1453.2  906.63
#Mann= 3 , 0 , 0
       0     .05       0   616.5    .045       0   665.3     .08       0
Bank Sta=616.5,665.3
XS Rating Curve= 0 ,0
Exp/Cntr=0.3,0.1

Type RM Length L Ch R = 1 ,19911.1 ,400.3,400,402.1
XS GIS Cut Line= 3
      1861751.56      637302.351     1862520.519      637025.816
     1863165.582      636881.184
#Sta/Elev= 30
       0  857.17    38.9  855.86    68.1  852.58   175.1  832.56   243.2  818.11
   282.1  811.83   301.6  806.31   369.7  780.51   379.4   777.4   389.1  775.86
   651.8  768.09   768.5  769.26   826.9   769.8   885.2  776.19   914.4   780.5
   972.7  793.72   992.2  799.86  1021.3   811.2  1040.8  821.04  1069.9  837.66
  1099.1  850.82  1128.3   860.3  1147.7  864.36  1167.2  867.26  1215.8  869.83
  1274.1  867.76    1313  864.65  1419.9   853.9  1439.4  851.24  1478.2   843.9
#Mann= 3 , 0 , 0
       0     .05       0   768.5    .045       0   826.9     .07       0
#Block Obstruct= 1 ,-1
   438.8   559.2  817.65
Bank Sta=768.5,826.9
XS Rating Curve= 0 ,0
Exp/Cntr=0.3,0.1

Type RM Length L Ch R = 1 ,19511.1 ,209,216.9,218.3
XS GIS Cut Line= 3
     1861724.978      637358.031     1862248.471      637281.002
     1863020.183      637265.298
#Sta/Elev= 30
       0  865.94    78.4  864.31      98  862.24   235.2  831.49     294  816.08
   313.6  809.37   372.4  782.79     392  775.74   440.9  770.87   509.5  766.93
   529.1  766.41   558.4  767.44   597.5  771.08   617.1  774.36   714.8  801.09
   753.8  806.57   783.2   813.2   812.5  821.88   841.8  832.22   871.1  843.35
     920   864.6   939.5  870.13   988.3  875.05  1017.7  874.98    1047  872.59
  1056.7  873.76  1144.7  906.16  1164.2  911.33  1252.2  930.22    1301  945.04
#Mann= 3 , 0 , 0
       0     .06       0   509.5    .045       0   558.4     .06       0
Bank Sta=509.5,558.4
XS Rating Curve= 0 ,0
Exp/Cntr=0.3,0.1

Type RM Length L Ch R = 1 ,19294.2 ,69.9,69.8,69.9
XS GIS Cut Line= 4
     1861748.482      637482.312     1862126.086      637469.291
     1862228.082      637464.951     1862783.638       637451.93
#Sta/Elev= 30
       0  870.27    29.1  869.31    67.8  865.18    77.5  862.97   116.2  851.85
   135.6  847.14   164.7  841.03   232.5  828.15   261.6  821.28   290.6  812.89
     310  806.07   329.4  798.23   339.1  793.63   358.4  782.55   368.1   778.2
   396.4  768.62   405.7  766.97     415  767.09   433.5  770.28   442.8  771.38
   509.2  774.64   548.2  778.24   635.9  796.14   665.2  803.29   694.4  808.69
   704.2  811.33   733.4  820.93   860.1  865.73   869.9  868.71  1035.6  907.37
#Mann= 3 , 0 , 0
       0     .05       0   396.4    .045       0   433.5     .05       0
Bank Sta=396.4,433.5
XS Rating Curve= 0 ,0
Exp/Cntr=0.3,0.1

Type RM Length L Ch R = 1 ,19224.4 ,118,113.3,112
XS GIS Cut Line= 4
     1861748.482      637551.756     1862126.086      637538.736
     1862228.082      637534.395     1862774.957      637512.694
#Sta/Elev= 30
       0  873.87    58.1  867.31    77.5  863.63     155  839.61   184.1  832.34
   242.2  819.44   271.3  811.67   377.8  777.11   396.4  769.31   405.7  767.28
     415  767.09   424.2  768.07   433.5  770.13   452.1  773.61   470.6  774.94
   509.2  773.55   528.8  773.79   548.3  776.29   577.6  782.06   616.7   792.1
   626.5  795.76   646.1  805.51   655.8  808.22   685.2  814.14   714.5  822.46
   841.5  864.11   851.3  866.47   880.6  870.83   909.9  876.88  1027.2  906.09
#Mann= 3 , 0 , 0
       0     .05       0   396.4    .045       0   433.5     .05       0
#Block Obstruct= 1 ,-1
  506.27  563.61  827.45
Bank Sta=396.4,433.5
XS Rating Curve= 0 ,0
Exp/Cntr=0.3,0.1

Type RM Length L Ch R = 1 ,19111.1 ,342.9,341.9,337.6
XS GIS Cut Line= 3
      1861746.09      637759.218      1862182.64      637647.154
      1862811.85      637588.649
#Sta/Elev= 30
       0  889.82   107.8  864.11   215.6  830.09   303.7  805.64   401.7  780.47
   411.5  777.53   431.1  770.26   440.9  767.63   450.7   766.9   489.6  768.28
   528.5     771   557.6  775.05   577.1  778.83   635.4  793.66   664.6  801.61
     684  808.09   713.2  820.15   771.5  845.83   800.7  855.71   820.1  859.86
   849.3  863.72   868.8  867.98   878.5  869.29   897.9  868.94   907.6  869.86
   917.4     872     966   884.1  1024.3  899.94  1053.5  909.61  1082.6  921.37
#Mann= 3 , 0 , 0
       0     .05       0   431.1    .045       0   489.6     .05       0
Bank Sta=431.1,489.6
XS Rating Curve= 0 ,0
Exp/Cntr=0.3,0.1

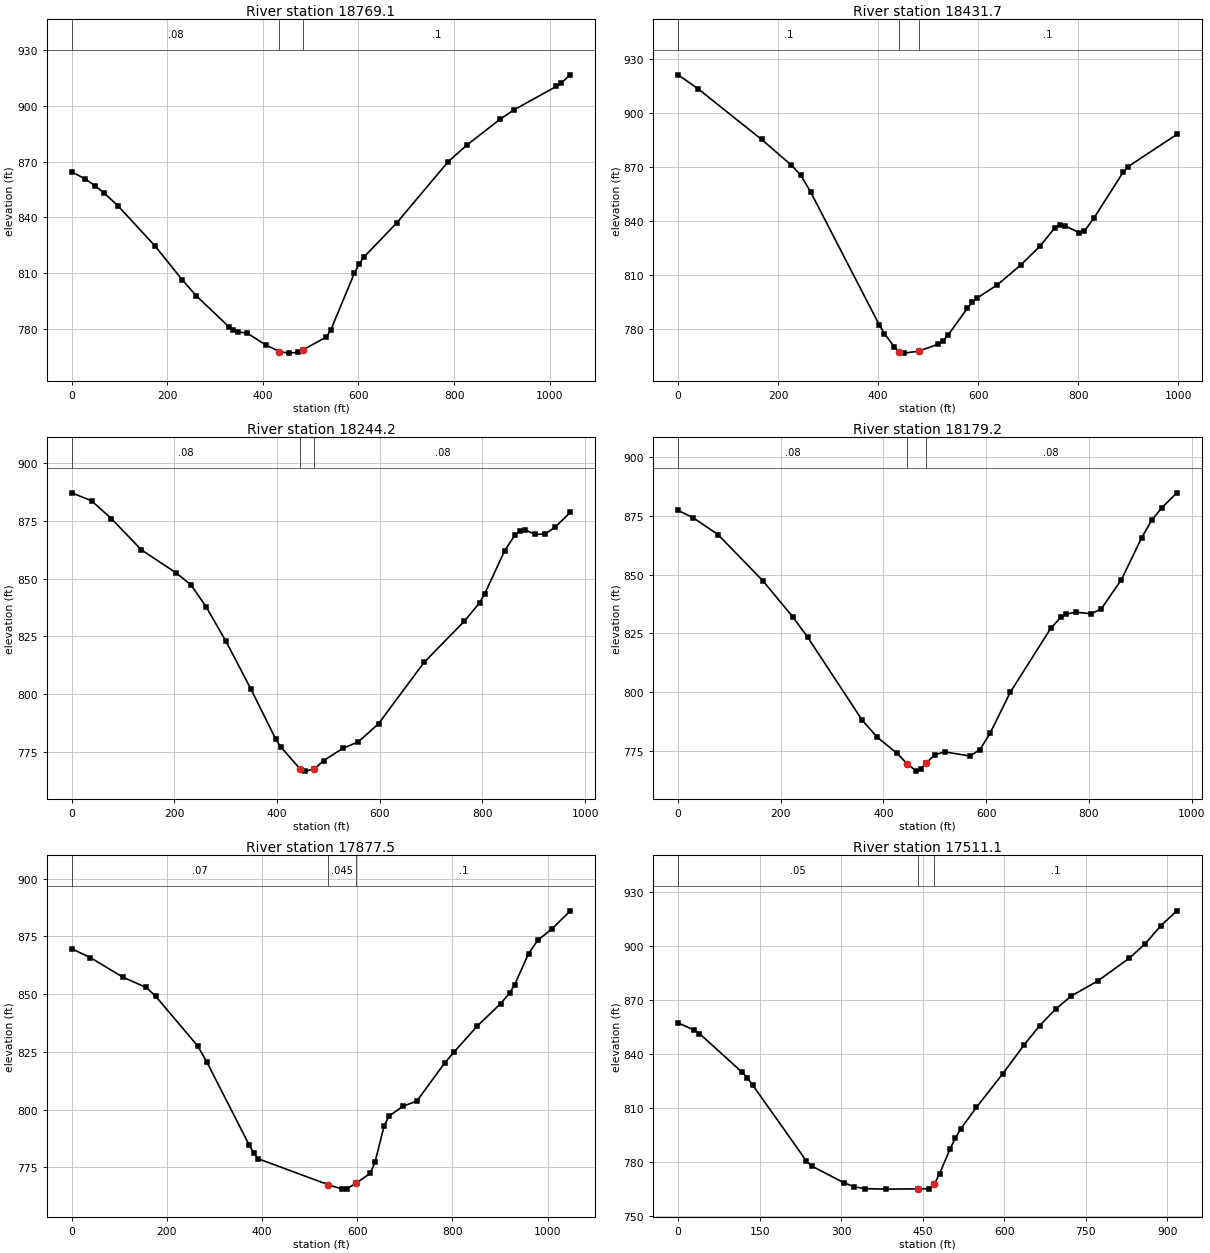
Type RM Length L Ch R = 1 ,18769.1 ,343.1,337.5,331.6
XS GIS Cut Line= 3
     1861846.991      638104.811     1862299.697      637966.253
     1862844.402      637799.152
#Sta/Elev= 30
       0  864.53      29  860.47    48.3  857.07    67.6  853.08    96.6  846.26
   173.9  824.66   231.9  806.14   260.9  797.64   328.5  781.11   338.2  779.04
   347.8  778.22   367.2  777.57   405.8  771.22   434.8  767.63   454.1   766.8
   473.4  767.25   483.3  768.46   532.4   775.4   542.2  779.33   591.3  809.76
   601.1  814.73     611  818.42   679.7  836.85   787.8  869.95   827.1  878.93
   895.8   892.7   925.3  897.82  1013.7  910.43  1023.6   912.2  1043.2  916.68
#Mann= 3 , 0 , 0
       0     .08       0   434.8    .045       0   483.3      .1       0
Bank Sta=434.8,483.3
XS Rating Curve= 0 ,0
Exp/Cntr=0.3,0.1

Type RM Length L Ch R = 1 ,18431.7 ,188,187.5,186.5
XS GIS Cut Line= 3
     1861967.329      638510.341      1862350.51      638270.887
     1862819.228      637991.861
#Sta/Elev= 30
       0  921.09    39.3  913.48     167  885.21   225.9  871.06   245.6  865.31
   265.2  855.95   402.7  782.01   412.6  777.43   432.2  770.05     442  767.34
   451.8  766.54   481.1  767.62     520   771.5   529.8  773.38   539.5  776.42
   578.5  791.48   588.2  794.67     598  797.14   636.9  804.16   685.6  815.54
   724.6  826.22   753.8   836.3   763.6  837.57   773.3  837.28   802.5  833.34
   812.3  834.26   831.7  841.63   890.2  867.09   899.9  870.15   997.3  887.98
#Mann= 3 , 0 , 0
       0      .1       0     442    .045       0   481.1      .1       0
Bank Sta=442,481.1
XS Rating Curve= 0 ,0
Exp/Cntr=0.3,0.1

Type RM Length L Ch R = 1 ,18244.2 ,65.1,65,65.1
XS GIS Cut Line= 4
     1862056.642      638660.263     1862433.378      638439.777
     1862494.142      638399.847     1862870.878      638132.486
#Sta/Elev= 30
       0   887.2    38.8  883.75    77.6  875.99   135.8  862.49   203.7  852.47
   232.8  847.22   261.9  837.79   300.7  822.78   349.2   802.1   397.7   780.3
   407.4  776.98   445.6  767.33   454.7  766.54   472.9   767.5     491  771.14
   528.9  776.49   558.4  779.24   597.7  787.11   686.2  813.66   764.8  831.55
   794.3   839.5   804.1  843.27   843.4  862.15   863.1  868.83   872.9  870.79
   882.7  871.19   902.4  869.16     922  869.34   941.7  872.35   971.2  878.76
#Mann= 3 , 0 , 0
       0     .08       0   445.6    .045       0   472.9     .08       0
Bank Sta=445.6,472.9
XS Rating Curve= 0 ,0
Exp/Cntr=0.3,0.1

Type RM Length L Ch R = 1 ,18179.2 ,312.6,301.7,289.9
XS GIS Cut Line= 4
     1862086.155      638717.555     1862462.892      638497.069
     1862523.655      638457.138     1862900.392      638189.777
#Sta/Elev= 30
       0  877.25    29.1  874.19    77.6  867.01   164.9  847.39   223.1  832.09
   252.2  823.39   358.9  787.98     388   780.8   426.8  773.93   445.6  769.64
   463.8  766.43   472.9  767.37     482  769.71   500.1  773.37     519  774.64
   568.2  772.85   587.9   775.6   607.5   782.5   646.8  799.92   725.5  827.07
   745.1   831.8     755  833.15   774.6     834   804.1  833.34   823.8  835.33
   863.1  847.72   902.4  865.48     922     873   941.7  878.33   971.2  884.73
#Mann= 3 , 0 , 0
       0     .08       0   445.6    .045       0     482     .08       0
Bank Sta=445.6,482
XS Rating Curve= 0 ,0
Exp/Cntr=0.3,0.1

Type RM Length L Ch R = 1 ,17877.5 ,355.4,366.5,378.8
XS GIS Cut Line= 3
     1862457.249      639130.316      1862715.93      638645.941
     1862945.096      638203.232
#Sta/Elev= 30
       0  869.63    39.2  865.79   107.9   857.3   156.9  852.85   176.5  849.07
   264.8  827.55   284.4  820.45   372.6  784.86   382.4  781.31   392.2  778.72
   539.3  767.52   568.7  765.61   578.4  765.78     598  768.24   627.3  772.45
   637.1  777.16   656.6  793.06   666.4  797.14   695.7  801.45   725.1  803.69
   783.7   820.2   803.3  824.94   852.1  836.18     901  845.84   920.6  850.59
   930.3  853.94   959.7  867.48   979.2  873.33  1008.5  878.14  1047.6  886.02
#Mann= 3 , 0 , 0
       0     .07       0   539.3    .045       0     598      .1       0
Bank Sta=539.3,598
XS Rating Curve= 0 ,0
Exp/Cntr=0.3,0.1

Type RM Length L Ch R = 1 ,17511.1 ,394.3,400,402.2
XS GIS Cut Line= 3
     1862614.802      639119.179     1862993.894      638855.837
     1863386.216      638623.535
#Sta/Elev= 30
       0  857.28    29.5  853.29    39.3  851.32   117.8  829.87   127.7  826.57
   137.5  822.63   235.7   780.7   245.5  777.78   304.4  768.54   324.1  766.18
   343.7  765.15     383  764.89   441.9  765.04   461.6  765.07   471.3  767.63
     481  773.43   500.4  787.24   510.1  793.27   519.8  798.33   548.9  810.36
   597.4  829.06   636.2  844.89   665.3  855.81   694.4  864.88   723.5  872.28
     772  880.57   830.2  893.26   859.3  901.21   888.4  911.37   917.5  919.55
#Mann= 3 , 0 , 0
       0     .05       0   441.9    .045       0   471.3      .1       0
Bank Sta=441.9,471.3
XS Rating Curve= 0 ,0
Exp/Cntr=0.3,0.1

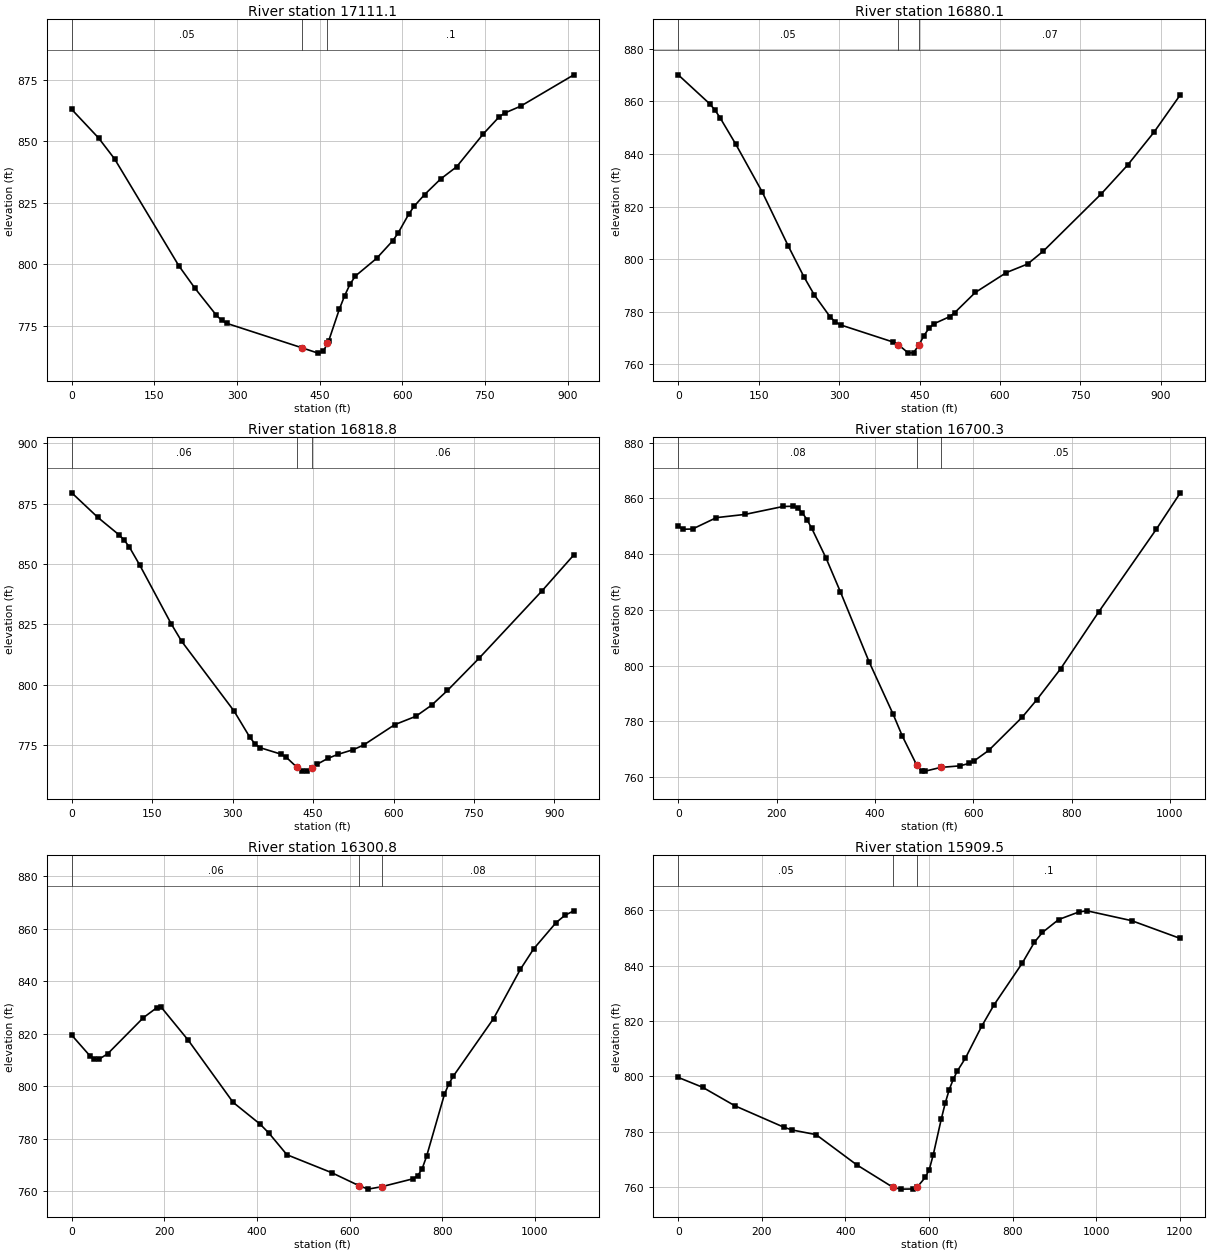
Type RM Length L Ch R = 1 ,17111.1 ,225,231,238.7
XS GIS Cut Line= 3
     1862754.531      639361.757     1863182.703      639202.851
     1863595.265      639011.689
#Sta/Elev= 30
       0  862.87    48.6  851.32    77.7  842.82   194.3  799.46   223.5  790.36
   262.4  779.39   272.1  777.29   281.8  776.05   417.8  766.17     447     764
   456.7  764.77   464.2  768.03   466.4  768.98   485.7  781.82   495.4  787.32
   505.1  791.98   514.8  795.28   553.4  802.46   582.5  809.56   592.2  812.65
   611.5  820.31   621.2  823.52   640.5  828.35   669.6  834.67   698.6  839.61
   746.9  852.92     776  859.92   785.6   861.4   814.7  864.19   911.4  876.93
#Mann= 3 , 0 , 0
       0     .05       0   417.8    .045       0   464.2      .1       0
Bank Sta=417.8,464.2
XS Rating Curve= 0 ,0
Exp/Cntr=0.3,0.1

Type RM Length L Ch R = 1 ,16880.1 ,61.3,61.3,61.3
XS GIS Cut Line= 4
     1862790.582      639448.024     1863200.305      639430.663
      1863372.18      639415.038     1863705.513      639296.982
#Sta/Elev= 30
       0  870.08    58.6  859.08    68.4  856.72    78.1  853.74   107.4  843.68
   156.2  825.72     205   805.1   234.3  793.36   253.9  786.39   283.2  778.12
   292.9  776.17   302.7  775.05   400.3  768.56   410.1  767.58   429.3  764.32
   438.8  764.52   448.4  767.22     458  770.91   467.6  773.77   477.2  775.51
     506  778.16   515.6  779.71   553.9  787.36   612.1  794.95   651.4  798.17
   680.9   803.1     789  824.87   838.1   835.8   887.2  848.27   936.3  862.49
#Mann= 3 , 0 , 0
       0     .05       0   410.1    .045       0   448.4     .07       0
Bank Sta=410.1,448.4
XS Rating Curve= 0 ,0
Exp/Cntr=0.3,0.1

Type RM Length L Ch R = 1 ,16818.8 ,128.4,118.5,110.1
XS GIS Cut Line= 4
     1862797.527      639508.788     1863207.249      639491.427
     1863379.124      639475.802     1863712.457      639357.746
#Sta/Elev= 30
       0  879.52    48.8  869.29    87.9  862.14    97.6  859.97   107.4  857.03
   126.9   849.5   185.5  825.16     205  817.92   302.7  789.01     332  778.18
   341.7  775.39   351.5  773.81   390.6  771.12   400.3   769.8   419.7  765.74
   429.3  764.16   438.8  764.11   448.4  765.41     458  767.01   477.2  769.36
   496.4  771.07   525.2  773.03   544.3  774.93   602.3  783.38   641.6  786.84
   671.1  791.46   700.6  797.56   759.5  810.91   877.4  838.98   936.3  853.78
#Mann= 3 , 0 , 0
       0     .06       0   419.7    .045       0   448.4     .06       0
Bank Sta=419.7,448.4
XS Rating Curve= 0 ,0
Exp/Cntr=0.3,0.1

Type RM Length L Ch R = 1 ,16700.3 ,412.2,399.5,384.9
XS GIS Cut Line= 3
     1862854.819      639845.593     1863281.902      639595.593
     1863752.388      639359.482
#Sta/Elev= 30
       0  850.09     9.7  848.92    29.1     849    77.6  853.08   135.8  854.24
   213.5  857.09   232.9  857.16   242.6  856.49   252.3  854.85     262  852.33
   271.7  849.21   300.8  838.52   329.9  826.46   388.1  801.43   436.6  782.79
   456.1  774.64   485.2   764.3   494.9  762.18   502.6  762.17   533.9   763.5
   572.9  764.06   592.4  764.97   602.1  765.87   631.4  769.58   699.6   781.5
   728.8  787.65   777.6  798.82   855.6  819.35   972.5  848.93  1021.3  861.98
#Mann= 3 , 0 , 0
       0     .08       0   485.2    .045       0   533.9     .05       0
Bank Sta=485.2,533.9
XS Rating Curve= 0 ,0
Exp/Cntr=0.3,0.1

Type RM Length L Ch R = 1 ,16300.8 ,386.6,391.3,396.2
XS GIS Cut Line= 4
     1863347.657      640359.077      1863584.81      639860.796
      1863649.74      639728.869     1863813.803       639379.91
#Sta/Elev= 30
       0   819.4    38.7  811.64    48.4  810.41    58.1  810.17    77.4  812.29
   154.9  826.12     184  829.92   193.6  829.99   251.7  817.46   348.5  793.79
   406.6  785.51     426  782.03   464.7  773.82   561.6  766.96   620.5  762.01
   640.1   760.7   669.5  761.63   737.4  764.65   747.1  765.77   756.7  768.41
   766.4  773.22   804.9  796.81   814.6  800.89   824.2   803.8     911  825.72
   968.8  844.46   997.7  852.32  1045.9  862.29  1065.2  865.12  1084.5  866.83
#Mann= 3 , 0 , 0
       0     .06       0   620.5    .045       0   669.5     .08       0
Bank Sta=620.5,669.5
XS Rating Curve= 0 ,0
Exp/Cntr=0.3,0.1

Type RM Length L Ch R = 1 ,15909.5 ,366.3,368.2,369.8
XS GIS Cut Line= 4
     1863584.636      640463.244     1863877.388      640076.496
     1863992.953      639934.958     1864335.721      639526.149
#Sta/Elev= 30
       0  799.64    58.2  796.08   135.8  789.37   252.2  781.69   271.6  780.68
   329.8  778.98   426.8   768.1   513.9  759.94   533.1   759.3     562  759.35
   571.6  759.99   590.8   763.5   600.5  766.31   610.1  771.66   629.3  784.56
   638.9  790.38   648.5  795.27   658.2  799.01   667.8  801.95   687.2  806.61
     726   818.1   755.1  825.71     823  840.87   852.1  848.42   871.5  851.99
   910.3  856.64   958.8  859.38   978.2  859.78  1084.9  856.23  1201.3   849.8
#Mann= 3 , 0 , 0
       0     .05       0   513.9    .045       0   571.6      .1       0
Bank Sta=513.9,571.6
XS Rating Curve= 0 ,0
Exp/Cntr=0.3,0.1

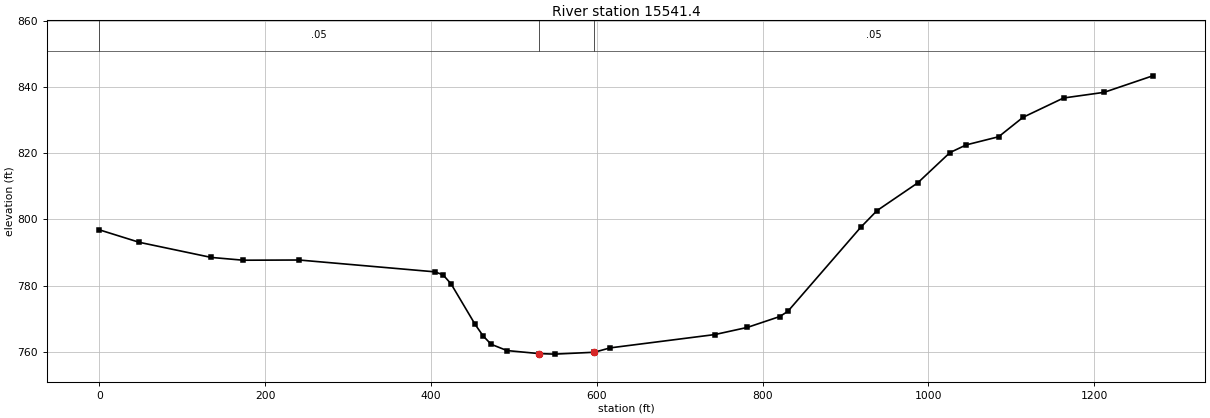
Type RM Length L Ch R = 1 ,15541.4 ,43.4,43.4,45.4
XS GIS Cut Line= 4
     1863821.073      640601.916     1864157.119      640269.667
     1864288.629      640130.344        1864713.      639696.968
#Sta/Elev= 30
       0  796.86    48.2  793.09     135  788.52   173.6  787.68   241.1  787.74
     405  784.16   414.7  783.24   424.3  780.52   453.3  768.28   462.9  764.82
   472.6  762.28   491.7  760.38     530  759.47   549.2   759.3   597.1  759.87
   616.2  761.19   742.4  765.21   781.6  767.37   820.7  770.65   830.5  772.22
   918.5  797.64   938.1  802.67     987  811.01  1026.1  820.21  1045.7  822.53
  1084.8  824.99  1114.2  830.86  1163.1   836.7    1212  838.41  1270.7   843.4
#Mann= 3 , 0 , 0
       0     .05       0     530    .045       0   597.1     .05       0
Bank Sta=530,597.1
XS Rating Curve= 0 ,0
Exp/Cntr=0.3,0.1