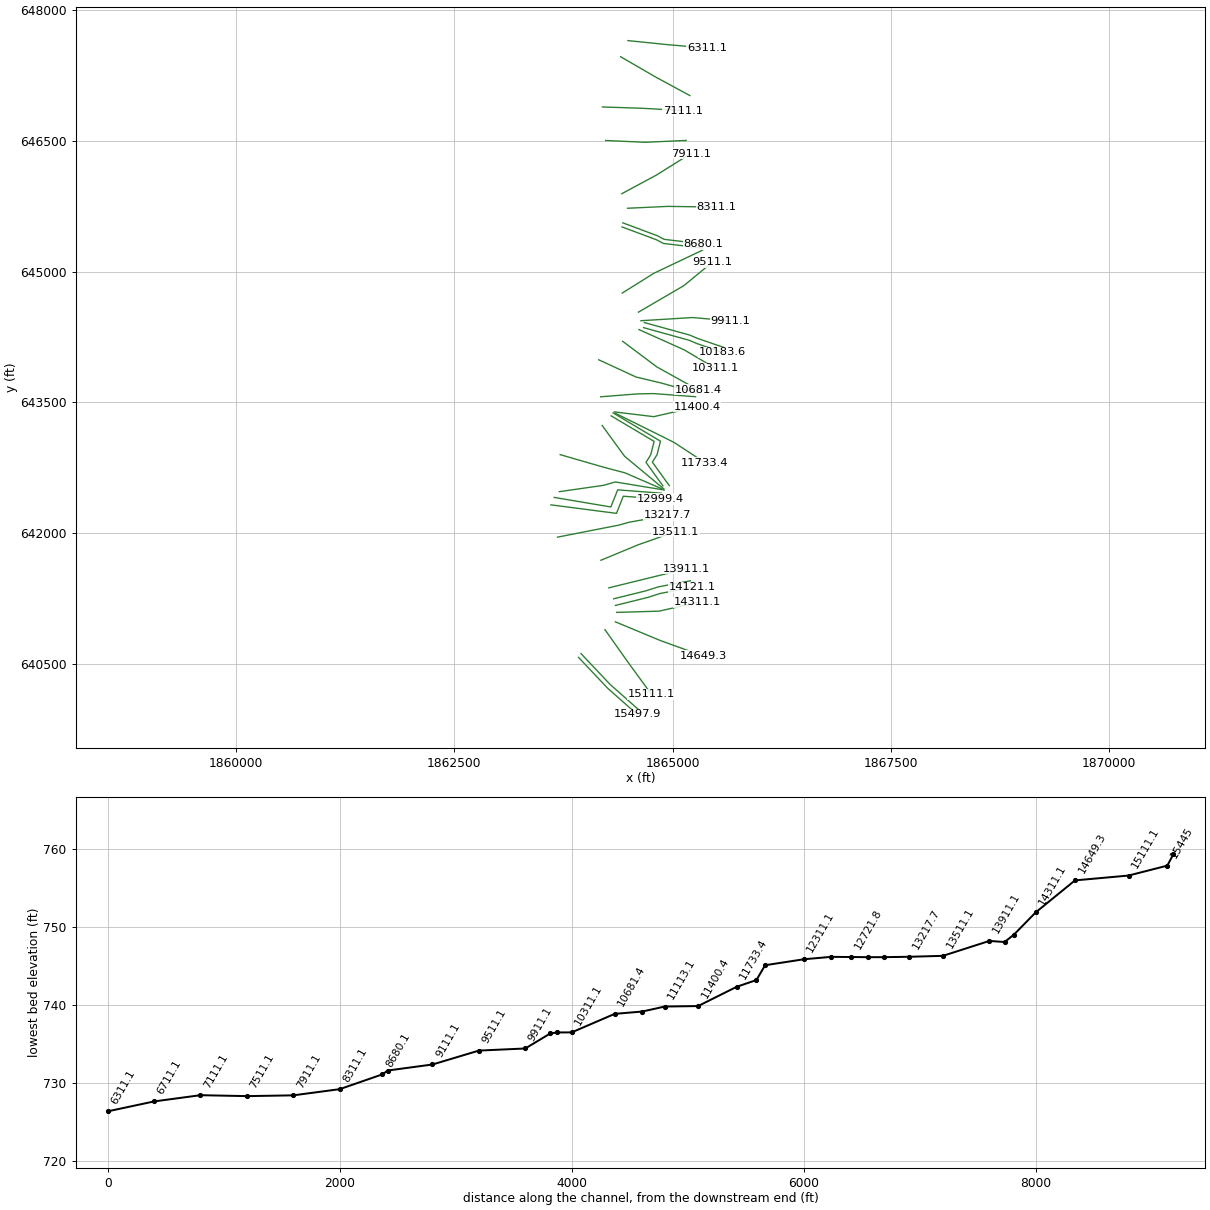
HEC-RAS study RFSpringCk.prj: RFSpringCk

--- RFSpringCk.g01 (geometry) --- (continued)

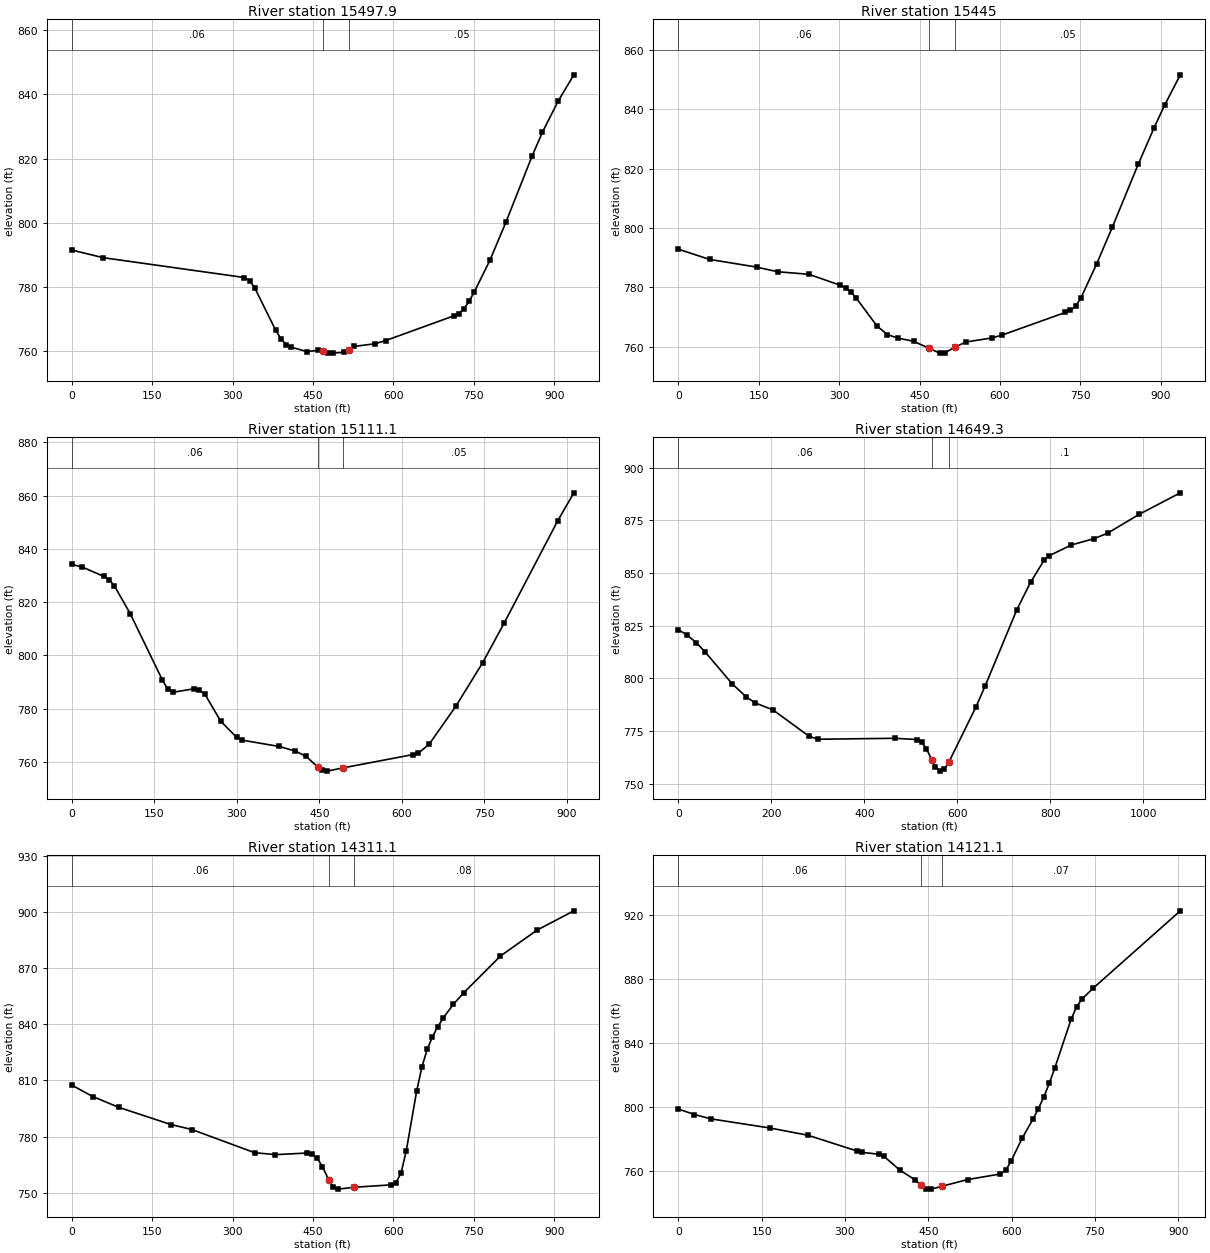
Type RM Length L Ch R = 1 ,15497.9 ,54,52.9,52.8
XS GIS Cut Line= 3
     1863922.128      640581.213     1864256.945      640226.699
     1864593.186      639929.512
#Sta/Elev= 30
       0  791.46    58.5  789.08   321.8  782.89   331.6  781.93   341.3  779.64
   380.4   766.4   390.1  763.78   399.9  761.95   409.6  761.14   438.9  759.76
   458.4  760.17   468.1  759.97   477.9  759.38   487.6   759.3   507.1  759.55
   516.9  760.36   526.6  761.39   565.7  762.23   585.2  763.21     712   770.9
   721.8  771.66   731.5  773.12   741.3  775.56     751  778.48   780.3  788.43
   809.6   800.1   858.3  820.68   877.8  828.22   907.1  837.92   936.4  846.13
#Mann= 3 , 0 , 0
       0     .06       0   468.1    .045       0   516.9     .05       0
Bank Sta=468.1,516.9
XS Rating Curve= 0 ,0
Exp/Cntr=0.3,0.1

Type RM Length L Ch R = 1 ,15445   ,335.9,334,329.3
XS GIS Cut Line= 3
      1863950.34      640624.616     1864285.157      640270.101
     1864621.398      639972.915
#Sta/Elev= 30
       0  792.87    58.5  789.41   146.3  786.82   185.3  785.26   243.8  784.39
   302.3  780.69   312.1  779.88   321.8  778.49   331.6  776.48   370.6  766.98
   390.1  764.07   409.6  762.88   438.9  761.82   468.1  759.42   487.6  757.82
   497.4  757.96   516.9  759.87   536.4  761.57   585.2  762.94   604.7  763.95
   721.8  771.52   731.5  772.23   741.3  773.66     751  776.42   780.3  787.86
   809.6  800.28   858.3  821.67   887.6  833.84   907.1   841.4   936.4  851.64
#Mann= 3 , 0 , 0
       0     .06       0   468.1    .045       0   516.9     .05       0
Bank Sta=468.1,516.9
XS Rating Curve= 0 ,0
Exp/Cntr=0.3,0.1

Type RM Length L Ch R = 1 ,15111.1 ,449,461.8,474.9
XS GIS Cut Line= 3
     1864225.246      640898.165     1864487.957      640527.319
     1864757.989      640157.393
#Sta/Elev= 30
       0  834.19    19.3  833.17      58   829.7    67.7  828.51    77.4  826.16
   106.4  815.61   164.4  790.89     174  787.47   183.7  786.16   222.4  787.47
   232.1  786.92   241.7  785.54   270.8  775.25   299.8  769.21   309.4  768.19
   377.1  765.81   406.1  764.08   425.5  762.16     447  758.12   454.5  756.89
   464.2  756.55   493.4  757.78   620.1  762.77   629.9  763.35   649.4   766.6
   698.1  780.94   746.8  797.28   785.8  812.13   883.2  850.56   912.5  861.06
#Mann= 3 , 0 , 0
       0     .06       0     447    .045       0   493.4     .05       0
Bank Sta=447,493.4
XS Rating Curve= 0 ,0
Exp/Cntr=0.3,0.1

Type RM Length L Ch R = 1 ,14649.3 ,328.7,338.2,351.5
XS GIS Cut Line= 3
     1864344.793      640987.663     1864864.042      640772.055
     1865350.153      640596.273
#Sta/Elev= 30
       0  823.14    19.4  820.46    38.8  816.93    58.2  812.41   116.3  797.29
   145.4  791.34   164.8  788.38   203.6  784.99   281.1  772.49   300.5  771.07
   465.3  771.52   513.8  770.92   523.5  769.55   533.2  766.65   545.4  761.22
   552.5  758.08   562.2  755.93     572  756.77   581.7   760.2   640.3  786.54
   659.8  796.42     728  832.65   757.3  845.58   786.6  856.12   796.3  858.09
   845.1   863.3   893.8  866.29   923.1  868.91   991.4  877.92  1079.2  888.05
#Mann= 3 , 0 , 0
       0     .06       0   545.4    .045       0   581.7      .1       0
Bank Sta=545.4,581.7
XS Rating Curve= 0 ,0
Exp/Cntr=0.3,0.1

Type RM Length L Ch R = 1 ,14311.1 ,183.6,190,191.8
XS GIS Cut Line= 3
     1864359.645      641095.816     1864846.489      641110.008
      1865284.69      641209.455
#Sta/Elev= 30
       0  807.52      39  801.41    87.7  795.61   185.1   786.4     224  783.75
   340.9  771.35   379.9   770.3   438.4  771.15   448.1  770.75   457.8  768.44
   467.6  763.78   479.6  756.63     487  753.14   496.8  751.84   526.1  752.83
   594.5   754.1   604.3  755.16     614   760.3   623.8  772.26   643.3  804.43
   653.1  817.32   662.9  826.62   672.6  833.31   682.4  838.66   692.2  843.22
   711.7   850.8   731.3  857.01   799.6  876.64     868  890.52   936.4  900.81
#Mann= 3 , 0 , 0
       0     .06       0   479.6    .045       0   526.1     .08       0
Bank Sta=479.6,526.1
XS Rating Curve= 0 ,0
Exp/Cntr=0.3,0.1

Type RM Length L Ch R = 1 ,14121.1 ,79.1,79.1,79.1
XS GIS Cut Line= 4
     1864345.378        641175.7     1864714.302      641266.846
     1864857.531      641312.419     1865224.285      641381.864
#Sta/Elev= 30
       0  799.03    29.2  795.58    58.5  792.87   165.6  787.12   233.9  782.58
   321.6   772.8   331.3   771.9   360.5  770.79   370.3  769.44   398.8  760.81
     427  754.59   436.4  751.45   445.8  749.35   455.2  748.96     474  750.69
   520.9  754.95   579.4   758.4   589.3  760.71   599.1   766.5   618.7  780.63
   638.4  792.64   648.2  799.22     658  806.62   667.8  815.12   677.7   824.6
   707.1  855.16     717  862.89   726.8  867.82   746.4  874.38   903.6  922.84
#Mann= 3 , 0 , 0
       0     .06       0   436.4    .045       0     474     .07       0
Bank Sta=436.4,474
XS Rating Curve= 0 ,0
Exp/Cntr=0.3,0.1

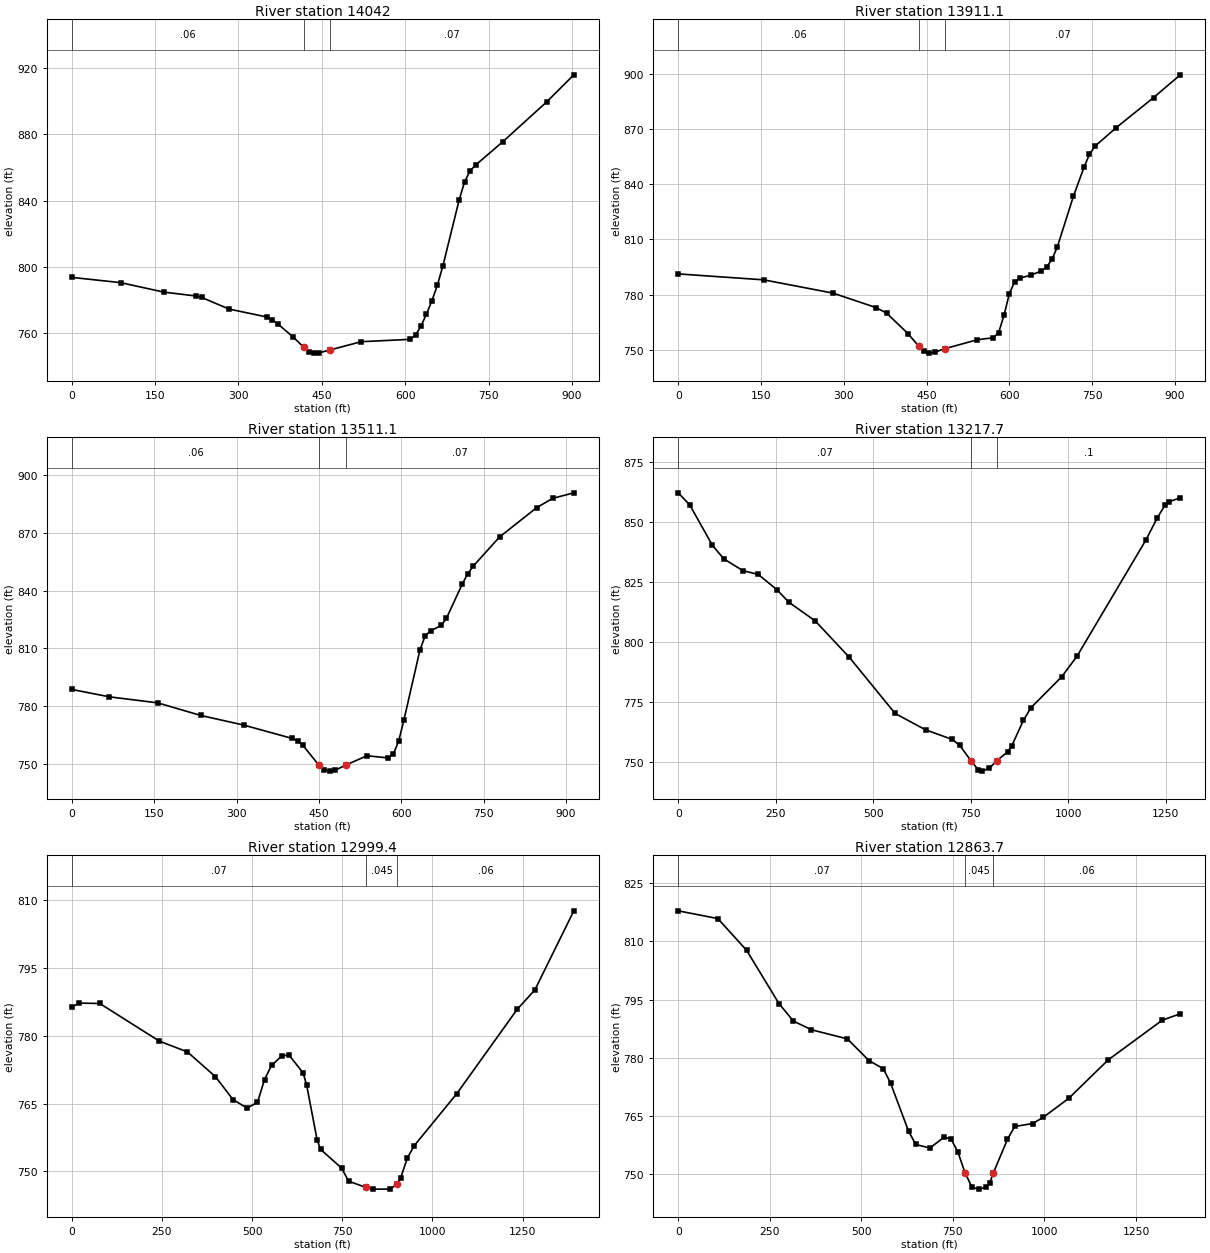
Type RM Length L Ch R = 1 ,14042   ,132.5,130.9,129.4
XS GIS Cut Line= 4
     1864325.847      641251.655     1864694.771      641342.801
        1864838.      641388.374     1865204.753      641457.818
#Sta/Elev= 30
       0  793.75    87.7  790.59   165.6  784.87   224.1  782.49   233.9  781.66
   282.6  774.67   350.8  769.87   360.5  768.24   370.3  765.82   398.8  757.65
   417.6  751.57     427  748.98   436.4  748.04   445.8  748.28   464.6  749.95
   520.9  754.94   608.9  756.36   618.7   758.9   628.6  764.42   638.4  771.64
   648.2  779.68     658  789.07   667.8  800.54   697.3  840.62   707.1  851.55
     717  858.11   726.8  861.53   775.9  875.67   854.5  899.59   903.6  915.99
#Mann= 3 , 0 , 0
       0     .06       0   417.6    .045       0   464.6     .07       0
Bank Sta=417.6,464.6
XS Rating Curve= 0 ,0
Exp/Cntr=0.3,0.1

Type RM Length L Ch R = 1 ,13911.1 ,396.5,400,402.2
XS GIS Cut Line= 3
     1864270.031      641377.059     1864711.927      641485.472
     1865153.822      641593.885
#Sta/Elev= 30
       0  791.19   154.9  787.97   280.7  780.75   358.2  772.94   377.6  769.93
   416.3  758.81   435.6  752.06   445.3  749.21     455  748.18   464.7  748.68
     484  750.66   542.1  755.45   571.2  756.54   580.8  759.35   590.5  768.82
   600.2  780.51   609.9  787.05   619.6  788.92   638.9   790.5   658.3  792.78
     668  795.05   677.7  799.27   687.3  806.03   716.4  833.49   735.7  849.29
   745.4  856.17   755.1  860.44   793.8  870.59   861.6  886.93     910  899.28
#Mann= 3 , 0 , 0
       0     .06       0   435.6    .045       0     484     .07       0
Bank Sta=435.6,484
XS Rating Curve= 0 ,0
Exp/Cntr=0.3,0.1

Type RM Length L Ch R = 1 ,13511.1 ,296.5,293.4,291.7
XS GIS Cut Line= 3
     1864179.476      641692.916     1864604.399      641869.373
     1865032.602      642020.528
#Sta/Elev= 30
       0  788.72    68.5  784.87   156.6  781.73     235  775.19   313.3  770.18
   401.4  763.25   411.2  761.99     421  759.62   450.3  749.25   460.1  746.84
   469.8  746.27   479.4  746.72   498.8  749.37   537.4  754.25     576  753.15
   585.7  755.23   595.4  762.06     605  773.09     634  809.27   643.7  816.67
   653.3  819.12   672.7  821.96   682.3  825.73   711.3  843.64     721  848.77
   730.6  852.64   778.9  867.92   846.6  883.18   875.6  887.98   914.2  890.86
#Mann= 3 , 0 , 0
       0     .06       0   450.3    .045       0   498.8     .07       0
Bank Sta=450.3,498.8
XS Rating Curve= 0 ,0
Exp/Cntr=0.3,0.1

Type RM Length L Ch R = 1 ,13217.7 ,175.8,218.2,253.2
XS GIS Cut Line= 4
     1863682.097      641957.732     1864390.431       642096.62
     1864499.806       642127.87      1864944.25      642207.732
#Sta/Elev= 30
       0  862.12    29.3  857.13    87.8   840.2     117  834.59   165.8  829.69
   204.8  828.16   253.6  821.66   282.9  816.61   351.2  808.74     439   793.5
     556  770.18     634  763.36   702.3  759.37   721.8  756.84   750.3  750.52
   769.2  746.67   778.7  746.15   797.7  747.39   816.6  750.47   845.4  754.31
   855.2  756.76   884.7  767.27   904.3  772.58   982.8  785.43  1022.1  793.98
  1198.8  842.43  1228.2  851.74  1247.9  856.96  1257.7  858.36  1287.1  860.07
#Mann= 3 , 0 , 0
       0     .07       0   750.3    .045       0   816.6      .1       0
Bank Sta=750.3,816.6
XS Rating Curve= 0 ,0
Exp/Cntr=0.3,0.1

Type RM Length L Ch R = 1 ,12999.4 ,150.9,135.7,126.2
XS GIS Cut Line= 4
     1863605.708      642327.523     1864357.444      642230.301
     1864435.569      642426.482     1864857.444      642395.232
#Sta/Elev= 30
       0  786.31    19.4  787.24    77.7  787.15     243  778.82   320.7  776.44
   398.4  770.97     447   765.9   485.9  764.03     515  765.29   534.5  770.34
   553.9  773.46   583.1  775.61   602.5  775.73   641.4  771.81   651.1  769.18
   680.2  757.03     690  754.88   748.3  750.75   767.6  747.86   815.6  746.48
   834.8   746.1   882.8   746.1     902  747.23   911.6   748.5   930.8  753.04
     950  755.74  1067.5   767.2  1234.8  785.83    1284  790.14  1392.2  807.64
#Mann= 3 , 0 , 0
       0     .07       0   815.6    .045       0     902     .06       0
Bank Sta=815.6,902
XS Rating Curve= 0 ,0
Exp/Cntr=0.3,0.1

Type RM Length L Ch R = 1 ,12863.7 ,168.5,141.9,116.6
XS GIS Cut Line= 4
     1863643.903      642412.593     1864293.208      642303.218
     1864371.333      642499.398     1864871.333      642461.204
#Sta/Elev= 30
       0  817.88   108.1  815.88   186.7   807.7   275.2  793.94   314.5  789.45
   363.6  787.21   461.9  784.85   520.9  779.25   560.2  777.15   579.8  773.45
     629  761.04   648.6  757.62   687.2   756.7   725.6  759.47   744.8  759.09
     764   755.6   783.2  750.31   802.4  746.55   821.6   746.1   840.8  746.59
   850.4  747.69     860  750.15   899.1  758.96   918.8  762.26   967.9  763.02
   997.4  764.66  1066.3  769.51  1174.4  779.45  1321.9  789.68  1371.1  791.33
#Mann= 3 , 0 , 0
       0     .07       0   783.2    .045       0     860     .06       0
Bank Sta=783.2,860
XS Rating Curve= 0 ,0
Exp/Cntr=0.3,0.1

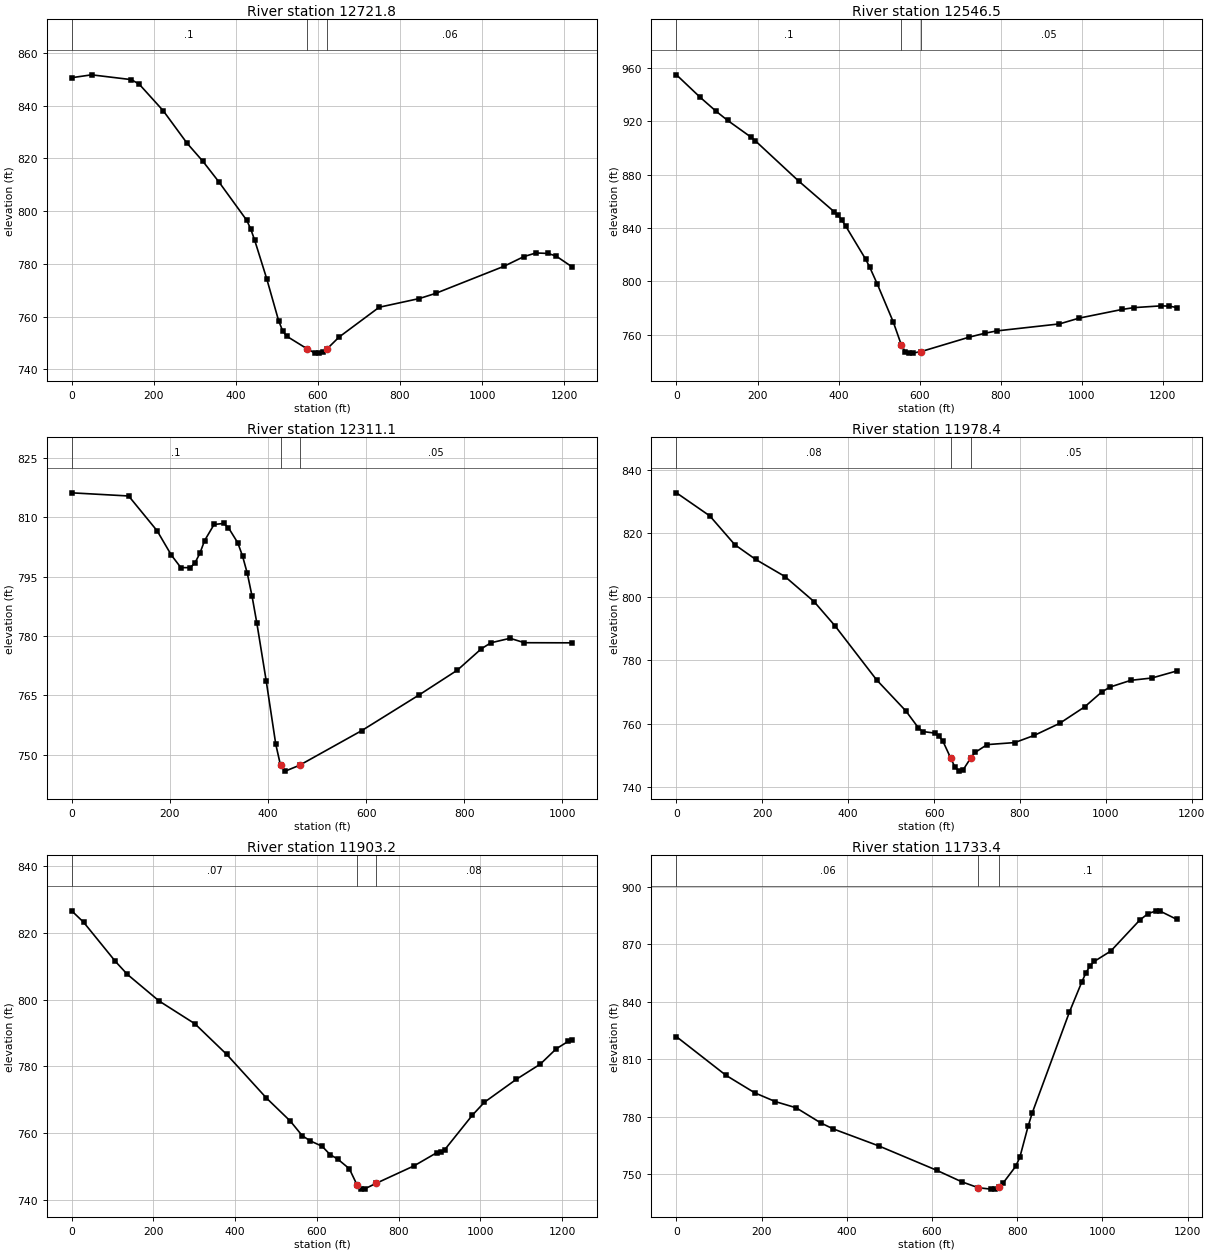
Type RM Length L Ch R = 1 ,12721.8 ,187.3,175.3,163.1
XS GIS Cut Line= 4
     1863702.931      642478.565     1864211.611      642551.482
     1864343.556      642589.676     1864904.319      642497.662
#Sta/Elev= 30
       0  850.57    48.5  851.66   145.4  849.84   164.8  848.06     223  838.05
   281.2   825.7     320   818.8   358.8  811.02   426.6  796.47   436.3  793.14
     446  788.86   475.1  774.37   504.2   758.4   513.9  754.61   523.7  752.55
   572.8  747.83   592.4  746.15   602.2  746.12     612  746.43   621.8  747.67
   651.2  752.18   749.2  763.52   847.2  766.83   886.4  768.76  1052.9  779.03
  1101.9  782.74  1131.3  784.11  1160.7  783.92  1180.3  782.93  1219.5  778.79
#Mann= 3 , 0 , 0
       0      .1       0   572.8    .045       0   621.8     .06       0
Bank Sta=572.8,621.8
XS Rating Curve= 0 ,0
Exp/Cntr=0.3,0.1

Type RM Length L Ch R = 1 ,12546.5 ,250.9,235.4,226.1
XS GIS Cut Line= 4
     1863712.479       642902.61     1864207.271      642759.381
     1864454.667      642694.277     1864880.014      642509.815
#Sta/Elev= 30
       0  954.88    58.3  938.08    97.2   927.7   126.4  920.65   184.7  907.96
   194.4  905.42   301.3  875.24   388.8  852.25   398.5  849.44   408.2  845.76
   417.9  841.22   466.5  816.66   476.2  810.96   495.7  797.74   534.8  769.52
   554.5  752.47   564.3  747.19   574.1  746.15   582.4  746.14   603.7  747.32
   721.7  758.09   761.1   761.1   790.2  762.81   944.8  768.06   993.1  772.38
  1099.3  778.91  1128.3  780.27  1195.9   781.6  1215.2  781.38  1234.6  780.31
#Mann= 3 , 0 , 0
       0      .1       0   554.5    .045       0   603.7     .05       0
Bank Sta=554.5,603.7
XS Rating Curve= 0 ,0
Exp/Cntr=0.3,0.1

Type RM Length L Ch R = 1 ,12311.1 ,352.9,332.7,306.3
XS GIS Cut Line= 3
     1864194.009      643236.012     1864450.327      642884.223
     1864900.089      642510.372
#Sta/Elev= 30
       0   816.2   116.1   815.4   174.1   806.6   203.1  800.45   222.5  797.29
   241.8  797.28   251.5  798.56   261.2  800.88   270.8  804.11   290.2   808.2
   309.5  808.45   319.2  807.43   338.5  803.56   348.2  800.21   357.9  795.84
   367.6  790.05   377.2  783.38   396.6  768.51   415.9  752.64   425.6   747.3
   435.3  745.83   464.5  747.32   591.2  756.08   708.2  765.11   786.2  771.38
   834.9  776.77   854.4  778.28   893.4  779.42   922.6   778.3  1020.1  778.27
#Mann= 3 , 0 , 0
       0      .1       0   425.6    .045       0   464.5     .05       0
Bank Sta=425.6,464.5
XS Rating Curve= 0 ,0
Exp/Cntr=0.3,0.1

Type RM Length L Ch R = 1 ,11978.4 ,75.2,75.2,75.2
XS GIS Cut Line= 5
     1864296.247      643347.055     1864788.868      643054.086
     1864749.372      642899.138     1864695.552      642814.068
     1864889.997      642544.971
#Sta/Elev= 30
       0   832.8    77.7  825.52     136  816.44   184.6   811.8   252.6  806.42
   320.6  798.49   369.2  790.88   466.3  773.81   534.3  764.04   563.4  758.73
   573.2  757.56   601.4  757.06   610.8  756.23   620.2  754.61     639   749.1
   648.4  746.37   657.8  745.07   667.2  745.39     686  749.33   695.4  750.95
   723.6  753.43     788  754.07   833.7  756.36   892.3  760.12   950.9  765.35
     990  769.96  1009.5  771.56  1058.3   773.7  1107.1  774.42  1165.7  776.66
#Mann= 3 , 0 , 0
       0     .08       0     639    .045       0     686     .05       0
Bank Sta=639,686
XS Rating Curve= 0 ,0
Exp/Cntr=0.3,0.1

Type RM Length L Ch R = 1 ,11903.2 ,138.1,169.8,201.4
XS GIS Cut Line= 5
     1864318.816      643380.909     1864861.785       643056.69
     1864822.288      642901.742     1864768.469      642816.673
     1864962.913      642547.575
#Sta/Elev= 30
       0  826.61    29.2  823.18     107  811.44   136.2  807.56     214  799.57
   301.6  792.74   379.4  783.56   476.7  770.47   535.1  763.56   564.3  759.18
   583.8  757.64   612.9  756.02   632.4  753.53   651.2  752.16   679.4   749.3
   698.2  744.48   707.6  743.17   717.1  743.24   745.3  744.92   838.1  750.16
     893  754.06   902.7  754.18   912.5  754.92   980.8  765.37  1010.1  769.22
  1088.3   776.1  1146.8  780.64  1185.9  785.24  1215.2  787.48    1225  787.89
#Mann= 3 , 0 , 0
       0     .07       0   698.2    .045       0   745.3     .08       0
Bank Sta=698.2,745.3
XS Rating Curve= 0 ,0
Exp/Cntr=0.3,0.1

Type RM Length L Ch R = 1 ,11733.4 ,317.5,333,348.4
XS GIS Cut Line= 4
     1864341.819       643377.87     1864836.611      643133.079
     1865020.205      643040.631     1865369.597      642811.898
#Sta/Elev= 30
       0  821.79   116.2  801.66     184   792.5   232.4  787.93   280.9  784.73
     339  776.81     368  773.72   474.6  764.88   610.8  752.16   669.5  746.17
   708.6  743.04     738  742.31   747.8  742.39   757.6   743.3   767.3  745.59
   796.4  754.15   806.2  758.87   825.6  775.06   835.3  782.01   922.7  834.66
   951.8  850.35   961.5  855.11   971.2  858.77     981  861.04  1019.8  866.43
  1087.8  882.58  1107.2  885.94  1126.6  887.41  1136.4  887.17  1175.2  882.91
#Mann= 3 , 0 , 0
       0     .06       0   708.6    .045       0   757.6      .1       0
Bank Sta=708.6,757.6
XS Rating Curve= 0 ,0
Exp/Cntr=0.3,0.1

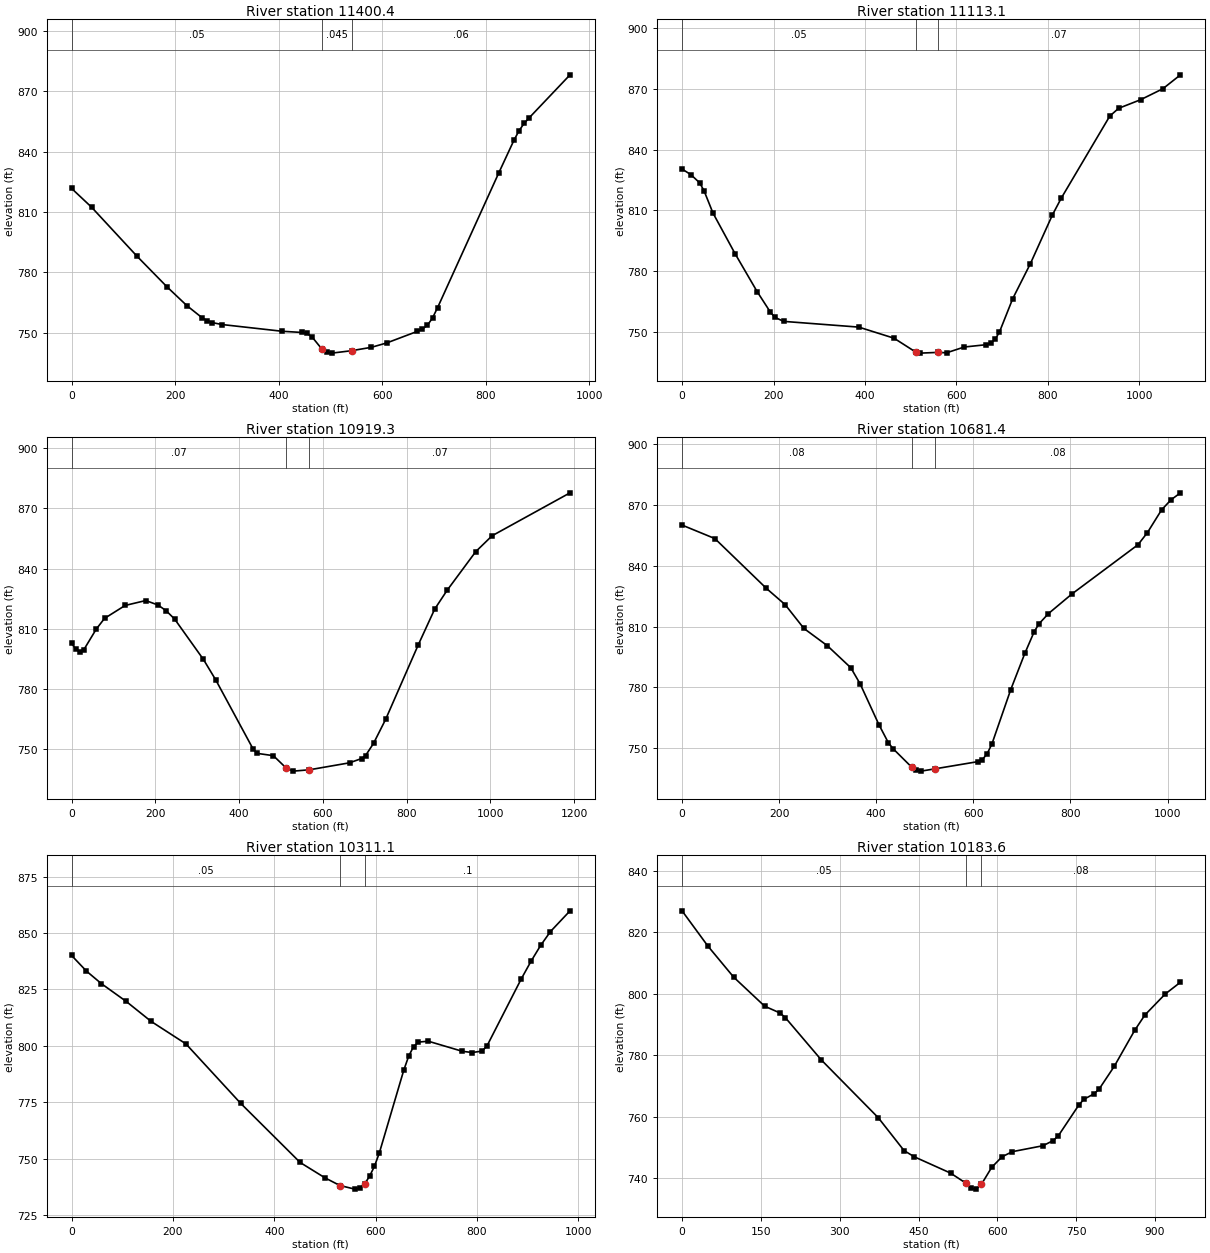
Type RM Length L Ch R = 1 ,11400.4 ,292.7,287.3,282.8
XS GIS Cut Line= 4
     1864332.705      643392.193     1864784.528      643337.506
     1864895.916      643363.049     1865279.523      643451.014
#Sta/Elev= 30
       0  821.73    38.7  812.37   125.9  788.15     184  772.88   222.7  763.46
   251.8   757.5   261.4  756.02   271.1  755.05   290.5  754.06   406.7  750.71
   445.4  750.11   455.1   749.6   464.6  747.87   483.7  741.83   493.2  740.17
   502.7  739.84   540.8  741.04   579.2  742.73   608.8   744.9   667.8  750.64
   677.6   751.8   687.5   753.7   697.3  757.32   707.2   762.5   825.2  829.38
   854.7  845.72   864.6  850.48   874.4  854.09   884.2  856.87     963  878.21
#Mann= 3 , 0 , 0
       0     .05       0   483.7    .045       0   540.8     .06       0
Bank Sta=483.7,540.8
XS Rating Curve= 0 ,0
Exp/Cntr=0.3,0.1

Type RM Length L Ch R = 1 ,11113.1 ,198.6,193.9,188.3
XS GIS Cut Line= 4
     1864176.889       643565.37     1864600.625      643598.552
     1864782.792      643601.829     1865264.102      643566.026
#Sta/Elev= 30
       0   830.4    19.3  827.65    38.6   823.6    48.3  819.59    67.6  808.75
   115.9  788.75   164.2  770.06   193.2  759.95   202.9   757.4   222.2  755.41
   386.4  752.59   463.4  747.14   511.3  740.25   520.9  739.78   559.3  740.14
   578.5  739.95   616.9  742.78   665.2  743.93   674.8  744.62   684.4  746.49
   694.1   750.2   723.1  766.62   761.7  783.84   809.9  807.84   829.2  816.08
   935.4  856.51   954.7   860.3    1003  864.56  1051.3  869.92  1089.9  876.78
#Mann= 3 , 0 , 0
       0     .05       0   511.3    .045       0   559.3     .07       0
Bank Sta=511.3,559.3
XS Rating Curve= 0 ,0
Exp/Cntr=0.3,0.1

Type RM Length L Ch R = 1 ,10919.3 ,246.7,237.8,232
XS GIS Cut Line= 4
     1864154.319      643988.982     1864583.139      643791.065
     1864862.653      643725.093     1865277.583      643608.773
#Sta/Elev= 30
       0  802.84     9.8   799.9    19.7   798.5    29.5  799.67      59  809.86
    78.7  815.17   127.9  821.61   177.1  824.05   206.6  821.81   226.3  818.89
     246  814.86   314.9  794.72   344.4   784.5   432.9  750.38   442.8  747.99
   481.9  746.83   512.3  740.72   529.7  739.14     568  739.81   663.8  743.28
   692.5   745.4     702  746.85   721.2  752.99   749.9  764.85     828  802.03
   867.2   819.8   896.6  829.08   965.2   848.4  1004.3   856.3  1190.4  877.67
#Mann= 3 , 0 , 0
       0     .07       0   512.3    .045       0     568     .07       0
Bank Sta=512.3,568
XS Rating Curve= 0 ,0
Exp/Cntr=0.3,0.1

Type RM Length L Ch R = 1 ,10681.4 ,363.7,370.4,370.2
XS GIS Cut Line= 3
     1864428.625      644200.787     1864822.722      643905.648
     1865289.981      643646.473
#Sta/Elev= 30
       0  859.92    67.6  853.28   173.8  828.75   212.4  820.76     251  809.06
   299.3  800.55   347.6  789.72   366.9  781.75   405.5  761.71   424.8  752.89
   434.4  749.94     473   740.8   482.7  739.22   492.4  738.84   521.5  739.99
   608.9  743.49   618.7  744.54   628.4   747.4   638.1  752.09     677  778.93
   706.1  796.81   725.5  807.53   735.2  811.32   754.7  816.36   803.2  826.04
   939.2  850.26   958.7  856.26   987.8  867.42  1007.3  872.39  1026.7  875.79
#Mann= 3 , 0 , 0
       0     .08       0     473    .045       0   521.5     .08       0
Bank Sta=473,521.5
XS Rating Curve= 0 ,0
Exp/Cntr=0.3,0.1

Type RM Length L Ch R = 1 ,10311.1 ,128.6,127.5,129.4
XS GIS Cut Line= 3
     1864614.698      644335.266     1865133.701       644102.58
     1865491.125      643891.759
#Sta/Elev= 30
       0  840.03    29.4  833.08    58.8  827.54   107.9  819.64   156.9  810.82
   225.6  800.85   333.4  774.56   451.1  748.28   500.1  741.47   529.6  738.07
     559  736.47   568.8  736.86   578.4  738.79   588.1   742.2   597.7  746.59
   607.4  752.55   655.6  789.21   665.3  795.42   674.9  799.65   684.6  801.63
   703.9  802.03   771.4  797.54   790.7  797.02     810  797.63   819.7  799.89
   887.2  829.54   906.5  837.38   925.8  844.52   945.1  850.63   983.7  859.81
#Mann= 3 , 0 , 0
       0     .05       0   529.6    .045       0   578.4      .1       0
Bank Sta=529.6,578.4
XS Rating Curve= 0 ,0
Exp/Cntr=0.3,0.1

Type RM Length L Ch R = 1 ,10183.6 ,58.4,57.6,57.6
XS GIS Cut Line= 4
     1864668.208      644357.037     1865189.042       644212.94
     1865279.319      644174.745     1865572.722      644074.051
#Sta/Elev= 30
       0  826.93    49.1  815.49    98.2  805.38   157.2  795.93   186.7   793.7
   196.5  792.22   265.3  778.41   373.4  759.68   422.5  748.99   442.1  746.96
   510.9  741.68   540.4  738.38   550.2   736.7     560  736.46   569.8  738.04
   589.4  743.56     609  746.98   628.6  748.64   686.9  750.57   706.3  752.25
     716  753.77   754.8  763.71   764.4  765.63   783.8  767.42   793.5  768.92
   822.6  776.39   861.4  788.07   880.8  793.05   919.5  799.88   948.6  803.73
#Mann= 3 , 0 , 0
       0     .05       0   540.4    .045       0   569.8     .08       0
Bank Sta=540.4,569.8
XS Rating Curve= 0 ,0
Exp/Cntr=0.3,0.1

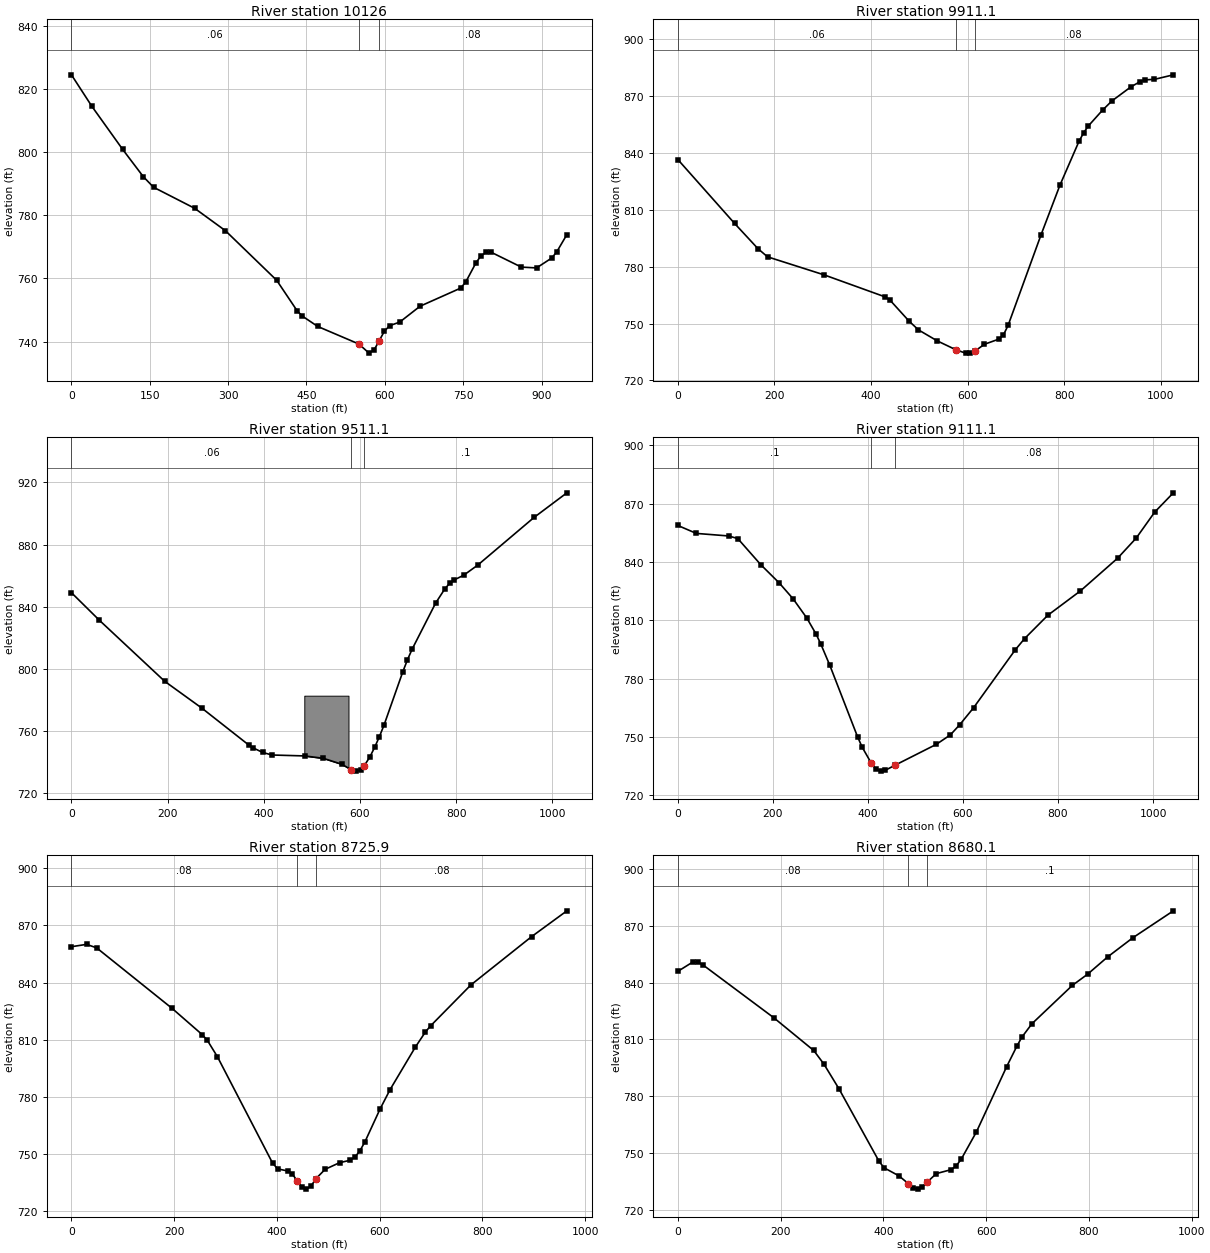
Type RM Length L Ch R = 1 ,10126   ,204.1,214.9,222
XS GIS Cut Line= 4
     1864676.889      644415.631     1865197.722      644271.534
        1865288.      644233.339     1865581.403      644132.645
#Sta/Elev= 30
       0  824.55    39.3  814.52    98.2  800.88   137.6  792.27   157.2  788.91
   235.8  782.25   294.8  775.14     393  759.41   432.3  749.71   442.1  748.06
   471.6  744.78   550.2  739.23   569.8  736.33   579.6  737.37   589.4  740.31
   599.2  743.28     609  745.01   628.6  746.18   667.5   751.2   745.1  756.93
   754.8  758.84   774.1  764.83   783.8  767.13   793.5  768.25   803.2  768.34
   861.4   763.6   890.5  763.34   919.5  766.47   929.2  768.44   948.6  773.91
#Mann= 3 , 0 , 0
       0     .06       0   550.2    .045       0   589.4     .08       0
Bank Sta=550.2,589.4
XS Rating Curve= 0 ,0
Exp/Cntr=0.3,0.1

Type RM Length L Ch R = 1 ,9911.1  ,389.5,400,417.5
XS GIS Cut Line= 3
     1864637.812      644436.659     1865232.415      644472.918
     1865660.858      644434.281
#Sta/Elev= 30
       0  836.36   117.2  802.78     166  789.38   185.6  785.14   302.7  775.64
   429.7  763.98   439.5  762.23   478.5  751.31     498  746.67   537.1  740.85
   576.2  736.11   595.7  734.41   605.5  734.59   615.3  735.54   634.8  739.09
   664.1  741.74   673.9  743.94   683.7  749.02   752.1  796.87   791.2  822.99
   830.4  845.92   840.1  850.48   849.9   854.1   879.2   862.4   898.8  867.29
   937.9  874.66   957.4   877.5   967.2  878.37   986.8  878.64  1025.9  881.02
#Mann= 3 , 0 , 0
       0     .06       0   576.2    .045       0   615.3     .08       0
Bank Sta=576.2,615.3
XS Rating Curve= 0 ,0
Exp/Cntr=0.3,0.1

Type RM Length L Ch R = 1 ,9511.1  ,399.2,400,394.1
XS GIS Cut Line= 3
     1864609.099      644534.554     1865128.469      644837.591
     1865460.166      645109.808
#Sta/Elev= 30
       0  848.99    58.2  831.21     194  791.94   271.6   774.6   368.6  750.99
   378.2  749.06   397.6  746.18     417  744.52   484.9  743.92   523.7   742.4
   562.5  738.53   581.9  735.03   591.6  734.14   601.3   734.9   608.8  737.48
   620.8  743.38   630.6  749.45   640.3  756.21   650.1  763.78   689.1  798.04
   698.8   805.8   708.6  812.68   757.4  842.28   776.8  851.57   786.6  855.02
   796.4  857.25   815.9  860.26   845.1  866.76   962.1  897.42  1030.4  913.26
#Mann= 3 , 0 , 0
       0     .06       0   581.9    .045       0   608.8      .1       0
#Block Obstruct= 1 ,-1
  484.28  576.19  782.71
Bank Sta=581.9,608.8
XS Rating Curve= 0 ,0
Exp/Cntr=0.3,0.1

Type RM Length L Ch R = 1 ,9111.1  ,408.5,385.2,364.1
XS GIS Cut Line= 3
     1864423.876      644753.365      1864785.57      644979.447
     1865342.125      645244.117
#Sta/Elev= 30
       0  858.74    38.8  854.67   106.6  853.36     126  852.02   174.5  838.56
   213.3  829.17   242.4  821.03   271.4  811.11   290.8  802.86   300.5  797.91
   319.9  786.71   378.1  750.04   387.8  744.69   407.2  736.38   416.8  733.35
   426.5  732.36   436.3  732.76   455.9  735.27   543.9  746.14   573.3  750.98
   592.8  756.13   622.2  764.93   710.2  794.82   729.8  800.58   778.7  812.58
   847.2  825.09   925.4   841.9   964.6  852.26  1003.7  865.68  1042.8  875.55
#Mann= 3 , 0 , 0
       0      .1       0   407.2    .045       0   455.9     .08       0
Bank Sta=407.2,455.9
XS Rating Curve= 0 ,0
Exp/Cntr=0.3,0.1

Type RM Length L Ch R = 1 ,8725.9  ,45.7,45.8,45.7
XS GIS Cut Line= 4
     1864421.247      645510.683     1864815.778      645363.548
     1864896.507      645321.447     1865345.726      645268.495
#Sta/Elev= 30
       0  858.86    29.4  860.09      49  858.27   195.8  826.51   254.6  812.69
   264.4  809.76     284  801.17   391.7  745.17   401.5  742.21   421.1  741.12
   430.2  739.47   439.3  735.95   448.4  732.64   457.5  731.59   466.6  733.27
   475.7  737.02   493.9  742.01     522  745.48   541.6  746.69   551.5  748.33
   561.3  751.64   571.1  756.32   600.6  773.58   620.3  783.88   669.4  806.15
   689.1  814.13     699  817.29   777.6  838.81   895.6  864.13   964.4   877.7
#Mann= 3 , 0 , 0
       0     .08       0   439.3    .045       0   475.7     .08       0
Bank Sta=439.3,475.7
XS Rating Curve= 0 ,0
Exp/Cntr=0.3,0.1

Type RM Length L Ch R = 1 ,8680.1  ,357.1,369.1,379.6
XS GIS Cut Line= 4
     1864429.927      645557.558     1864824.458      645410.423
     1864905.188      645368.322     1865354.406       645315.37
#Sta/Elev= 30
       0  845.92    29.4  850.89    39.2   850.7      49  849.24   186.1  821.56
   264.4  804.18     284   797.1   313.4  784.04   391.7  745.67   401.5  742.32
   430.2   738.1   448.4  734.04   457.5  731.84   466.6   731.1   475.7  732.29
   484.8  734.68     503  739.29   531.8  741.36   541.6  743.33   551.5  746.89
     581  761.23     640  795.71   659.6  806.36   669.4  811.16   689.1  818.28
   767.8  838.51   797.3  844.37   836.6  853.54   885.8  863.66   964.4  877.81
#Mann= 3 , 0 , 0
       0     .08       0   448.4    .045       0   484.8      .1       0
Bank Sta=448.4,484.8
XS Rating Curve= 0 ,0
Exp/Cntr=0.3,0.1

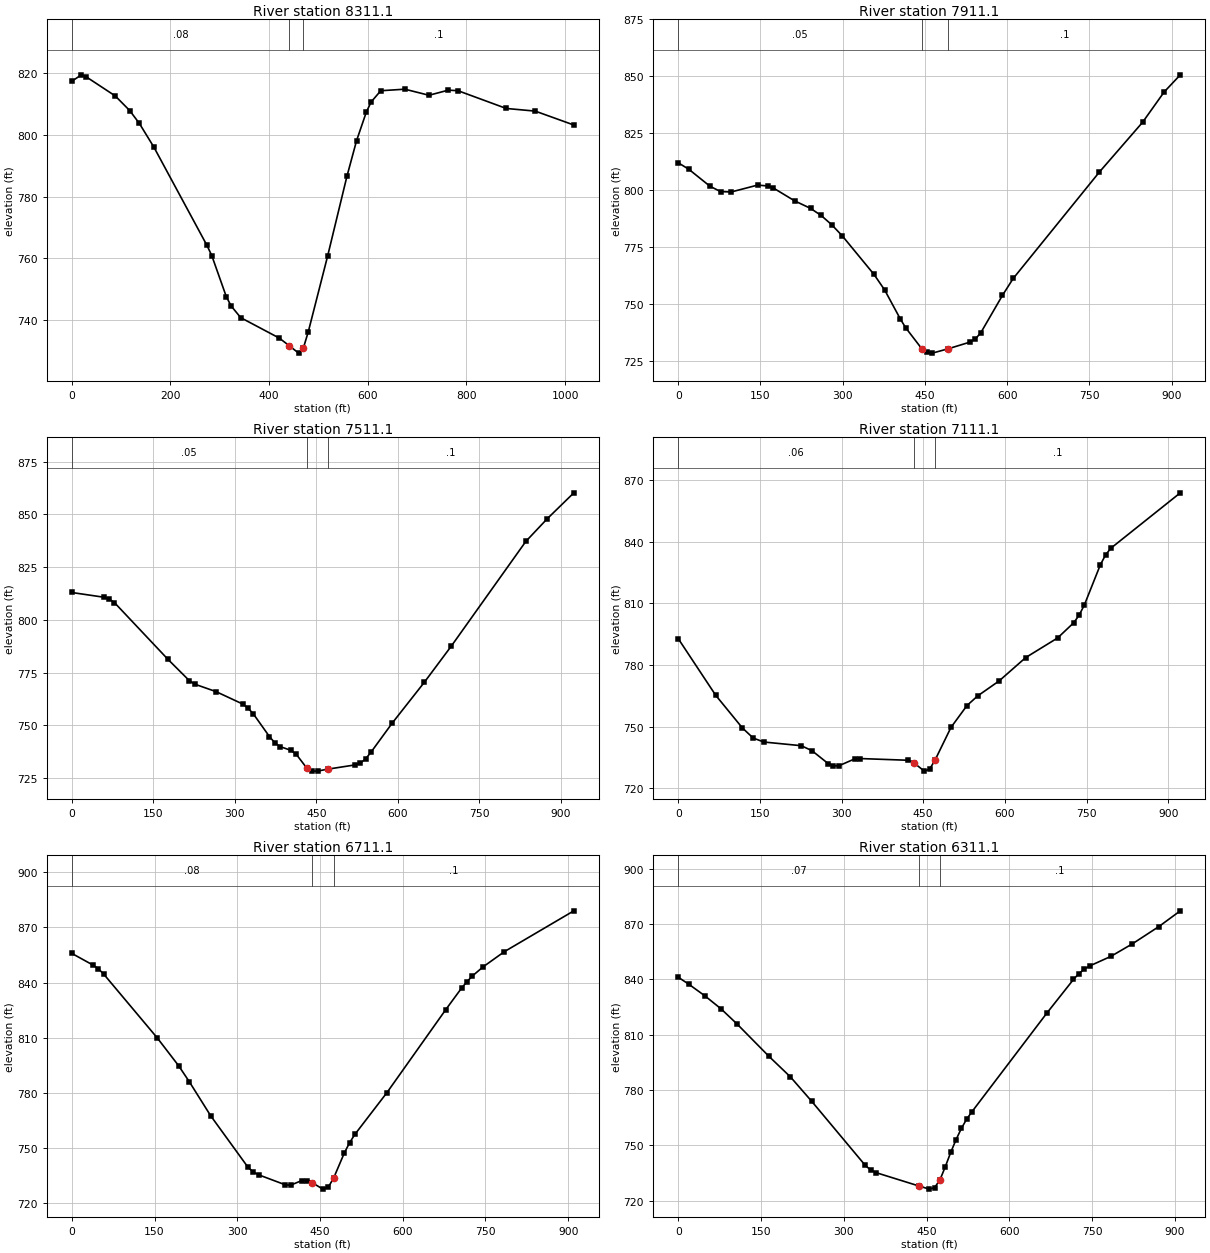
Type RM Length L Ch R = 1 ,8311.1  ,389.8,400,413
XS GIS Cut Line= 3
     1864484.198      645724.547     1864943.672      645745.963
     1865501.542      645738.548
#Sta/Elev= 30
       0  817.39    19.6  819.48    29.4  818.82    88.1  812.64   117.4   807.9
     137  803.72   166.4  796.05     274  764.17   283.8  760.86   313.2  747.56
     323  744.52   342.5  740.71   420.8  734.07   440.4  731.66     460   729.2
   469.8  730.99   479.6  736.18   518.7  760.68   557.8  786.52   577.4  798.13
     597  807.32   606.8  810.65   626.4  814.32   675.3  814.82   724.2  812.85
   763.4  814.51     783  814.33   880.9  808.57   939.6  807.71  1017.9   803.2
#Mann= 3 , 0 , 0
       0     .08       0   440.4    .045       0   469.8      .1       0
Bank Sta=440.4,469.8
XS Rating Curve= 0 ,0
Exp/Cntr=0.3,0.1

Type RM Length L Ch R = 1 ,7911.1  ,412,400,388.2
XS GIS Cut Line= 3
     1864418.284      645891.095     1864817.722      646106.026
     1865209.354      646351.273
#Sta/Elev= 30
       0  812.03    19.3  809.18    57.9  801.72    77.2  799.38    96.5   799.2
   144.8  802.23   164.1  801.83   173.7  800.92   212.3   795.3   241.3     792
   260.6  788.89   279.9  784.82   299.2  779.92   357.1  762.97   376.4  756.19
   405.3   743.3     415   739.5   443.9  730.44   453.6  728.71   463.4  728.41
   492.9  730.36   532.2  733.26   542.1  734.68   551.9   737.4   591.2  753.74
   610.9   761.2   768.2  807.99   846.9  829.82   886.2  843.13   915.7  850.67
#Mann= 3 , 0 , 0
       0     .05       0   443.9    .045       0   492.9      .1       0
Bank Sta=443.9,492.9
XS Rating Curve= 0 ,0
Exp/Cntr=0.3,0.1

Type RM Length L Ch R = 1 ,7511.1  ,399.8,400,397.6
XS GIS Cut Line= 3
     1864233.887      646500.649     1864685.502      646480.149
     1865156.575      646501.334
#Sta/Elev= 30
       0  812.99      59  810.75    68.8  809.87    78.6  808.17   176.9  781.31
   216.2  771.21     226  769.56   265.4     766   314.5  760.11   324.3  758.18
   334.2  755.38   363.6  744.71   373.5  741.74   383.3  739.93   402.9  738.19
   412.8  736.34   432.4  729.72   442.2  728.31   452.1  728.33   471.7  729.28
   520.8  731.24   530.7  732.08   540.5  734.11   550.3  737.24   589.6  751.12
   648.6  770.44   697.7  787.41   835.2  837.18   874.5  847.92   923.6  860.24
#Mann= 3 , 0 , 0
       0     .05       0   432.4    .045       0   471.7      .1       0
Bank Sta=432.4,471.7
XS Rating Curve= 0 ,0
Exp/Cntr=0.3,0.1

Type RM Length L Ch R = 1 ,7111.1  ,411.2,400,390
XS GIS Cut Line= 3
     1864196.326      646884.665     1864648.153      646869.873
     1865117.537       646843.84
#Sta/Elev= 30
       0  792.88    68.8  765.34   117.9  749.42   137.6  744.54   157.2  742.59
     226   740.8   245.7  738.36   275.2  732.14     285  731.02   294.8     731
   324.3  734.41   334.1  734.55   422.6  733.71   432.4  732.53   452.1  728.43
   461.9  729.44   471.7   733.8     501  749.71   530.4  760.35     550  765.02
   589.2  772.27   638.2  783.67   696.9  793.23   726.3  800.58   736.1  804.18
   745.9  809.22   775.3  828.79   785.1  833.69   794.8  836.91   922.2  863.82
#Mann= 3 , 0 , 0
       0     .06       0   432.4    .045       0   471.7      .1       0
Bank Sta=432.4,471.7
XS Rating Curve= 0 ,0
Exp/Cntr=0.3,0.1

Type RM Length L Ch R = 1 ,6711.1  ,390.4,400,409.3
XS GIS Cut Line= 3
     1864404.663      647460.367     1864798.388      647231.841
      1865198.44      647015.172
#Sta/Elev= 30
       0  855.86    38.7  849.46    48.4  847.42    58.1  844.51     155  809.87
   193.7  794.75   213.1  786.04   251.8  767.54   319.6  739.47   329.3   736.9
     339  735.39   387.4  729.94   397.1  729.82   416.5  732.24   426.2  732.28
   435.9  731.12   455.2  727.63   464.9  728.66   474.6  733.55     494  747.23
   503.6  752.85   513.3  757.43   571.4  780.14   677.9  825.22   706.9  837.07
   716.6  840.51   726.3  843.58   745.6   848.5   784.4  856.82   910.2     879
#Mann= 3 , 0 , 0
       0     .08       0   435.9    .045       0   474.6      .1       0
Bank Sta=435.9,474.6
XS Rating Curve= 0 ,0
Exp/Cntr=0.3,0.1

Type RM Length L Ch R = 1 ,6311.1  ,171.9,170.1,167.9
XS GIS Cut Line= 3
     1864488.698      647644.743     1864941.404       647598.48
     1865394.684      647559.088
#Sta/Elev= 30
       0  841.12    19.4  837.29    48.4  831.02    77.5  824.02   106.5  815.83
   164.6  798.22   203.3  787.16   242.1  773.86   338.9  739.25   348.6  736.76
   358.2  735.32   435.7  728.11   455.1  726.36   464.7   727.2   474.4   731.4
   484.1  738.54   493.8  746.21   503.5  753.13   513.2  759.25   522.8  764.28
   532.5  768.34     668  821.66   716.4  839.94   726.1  843.06   735.8  845.45
   745.5  847.21   784.2  852.43   822.9  859.17   871.3   868.6     910  877.09
#Mann= 3 , 0 , 0
       0     .07       0   435.7    .045       0   474.4      .1       0
Bank Sta=435.7,474.4
XS Rating Curve= 0 ,0
Exp/Cntr=0.3,0.1