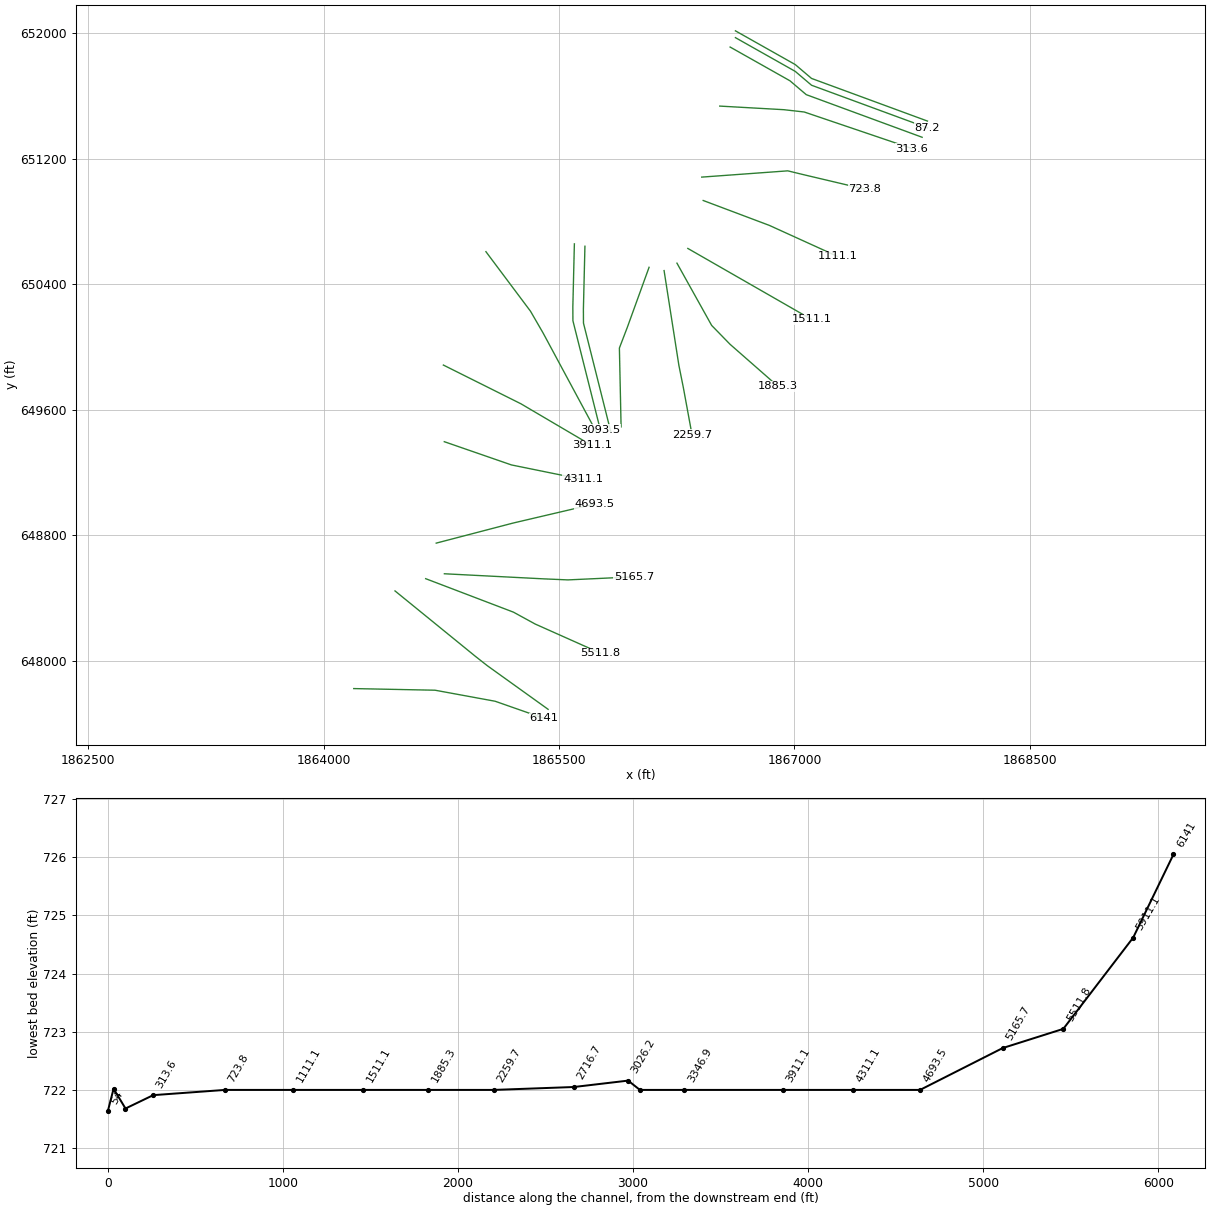
HEC-RAS study RFSpringCk.prj: RFSpringCk

--- RFSpringCk.g01 (geometry) --- (continued)

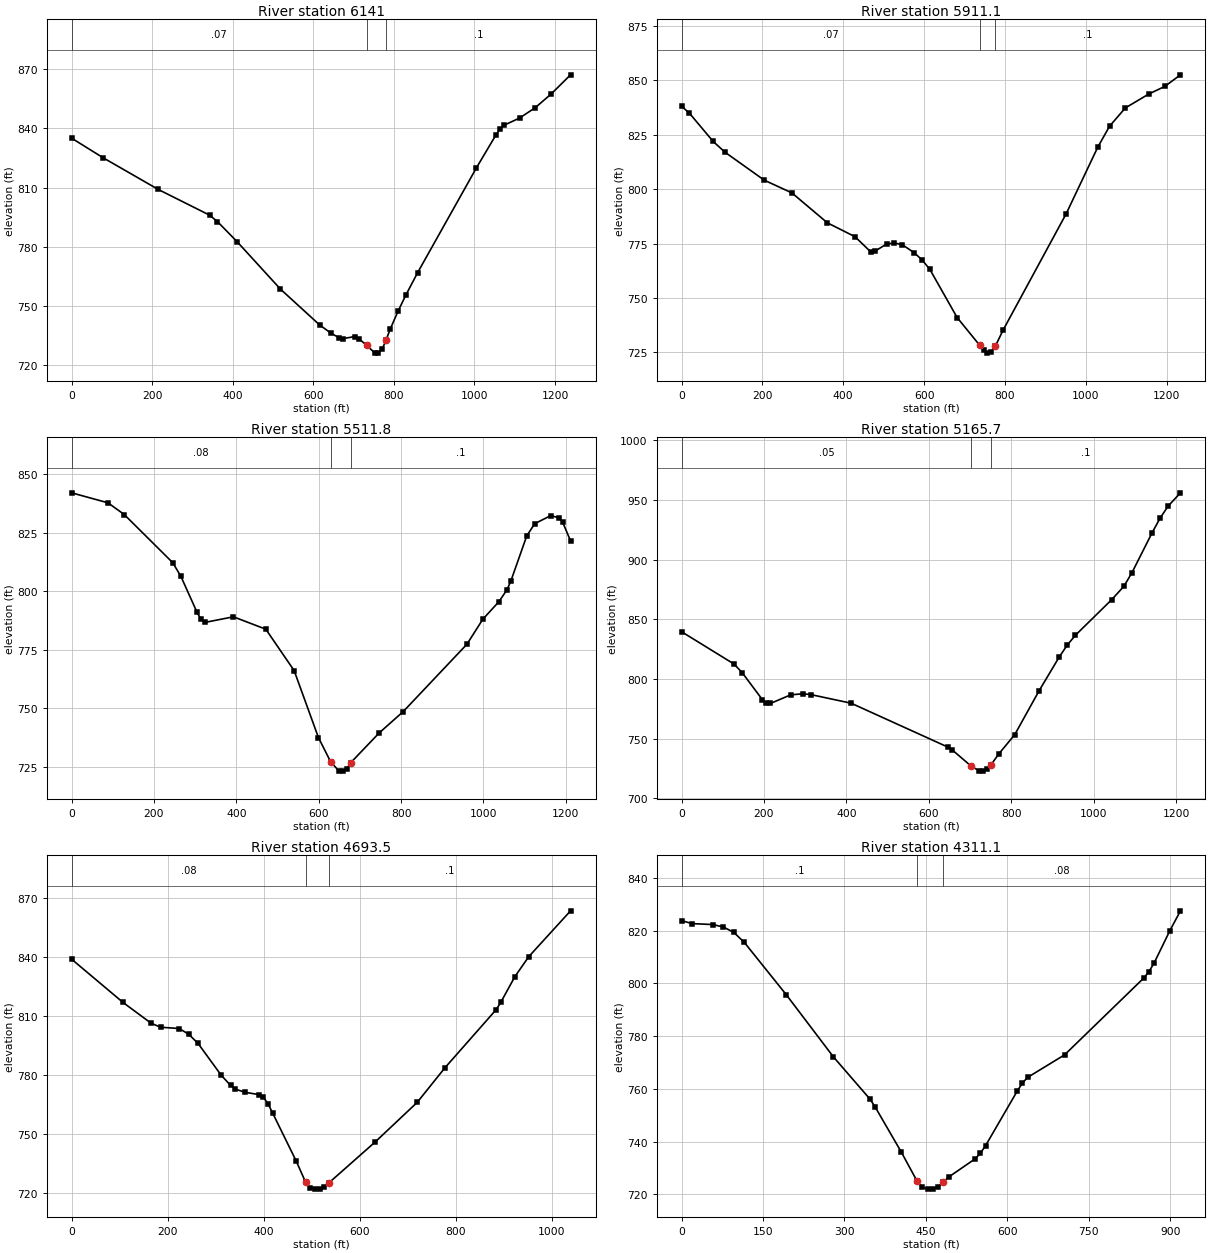
Type RM Length L Ch R = 1 ,6141    ,240.9,229.9,219.7
XS GIS Cut Line= 4
     1864191.212      647822.749     1864709.441      647812.332
     1865092.253       647742.02     1865404.753      647632.645
#Sta/Elev= 30
       0  835.02    78.2  825.09   215.2  809.01   342.3  796.02   361.9  792.75
   410.8  782.55   518.3  758.52   615.6  740.35   644.8  736.02   664.3  733.83
     674  733.41   703.2  734.46   712.9  733.44   732.4  729.94   751.9  726.31
   761.6  726.05   771.3  728.26     781  732.89   790.8  738.18   810.2  747.25
   829.7  755.48   858.9  766.83  1004.9  819.98  1053.6  836.74  1063.4  839.58
  1073.1  841.54    1112  845.22    1151  850.49    1190  857.34  1238.6  867.13
#Mann= 3 , 0 , 0
       0     .07       0   732.4    .045       0     781      .1       0
Bank Sta=732.4,781
XS Rating Curve= 0 ,0
Exp/Cntr=0.3,0.1

Type RM Length L Ch R = 1 ,5911.1  ,395.6,399.2,401.8
XS GIS Cut Line= 4
     1864454.233      648445.145     1864968.486      648026.732
     1865042.104      647968.895     1865430.102      647690.544
#Sta/Elev= 30
       0   838.1    19.5   834.9      78  821.95   107.2     817   204.7   804.1
     273  798.26   360.7  784.51     429  778.14     468  771.16   477.7   771.4
     507  774.72   526.5  775.25     546  774.44   575.2  770.81   594.7  767.51
   614.2  763.12   681.7  740.98   737.9  728.13   747.2  725.87   756.6  724.62
   766.3  725.27   776.1  727.79   795.6  735.27   951.5   788.7  1029.4  819.21
  1058.7  828.91  1097.7   837.3  1156.1  843.74  1195.1  847.16  1234.1  852.52
#Mann= 3 , 0 , 0
       0     .07       0   737.9    .045       0   776.1      .1       0
Bank Sta=737.9,776.1
XS Rating Curve= 0 ,0
Exp/Cntr=0.3,0.1

Type RM Length L Ch R = 1 ,5511.8  ,335.6,346.1,356.6
XS GIS Cut Line= 4
     1864649.545       648523.27     1865209.441      648309.728
     1865347.462      648234.207     1865762.826      648048.877
#Sta/Elev= 30
       0  842.13    88.4  837.85   127.7  832.85   245.6  812.23   265.2  806.42
   304.5  791.01   314.4  787.93   324.2   786.7   392.9  789.08   471.5  783.77
   540.3  766.06   599.2  737.43   628.7  727.11   648.4  723.21   658.2  723.05
   668.1  724.06   677.9   726.7   746.7  739.39     805  748.51   959.8  777.35
   998.5  788.07  1037.2  795.51  1056.6  800.53  1066.2  804.27    1105  823.69
  1124.3  828.93    1163  832.35  1182.4  831.51    1192  829.65  1211.4  821.56
#Mann= 3 , 0 , 0
       0     .08       0   628.7    .045       0   677.9      .1       0
Bank Sta=628.7,677.9
XS Rating Curve= 0 ,0
Exp/Cntr=0.3,0.1

Type RM Length L Ch R = 1 ,5165.7  ,465.2,472.2,477.2
XS GIS Cut Line= 4
     1864768.903       648554.52     1865404.753      648521.968
     1865556.663      648515.457      1865977.67      648534.989
#Sta/Elev= 30
       0  839.57   127.3  812.47   146.9  805.35   195.9  782.73   205.7  779.76
   215.5  779.42   264.5   786.6   293.8  787.56   313.4  786.88   411.4  779.64
   646.2  742.83   655.7  740.76   703.2  726.69   722.2  722.94   731.7  722.72
   741.2   724.3   750.7  728.05   769.7   737.2   808.3  753.34   867.1  789.96
   916.2  818.41   935.8  828.45   955.4  836.59  1043.6  866.49    1073  877.62
  1092.6  889.07  1141.6  922.62  1161.2  934.99  1180.8  945.02  1210.2  955.94
#Mann= 3 , 0 , 0
       0     .05       0   703.2    .045       0   750.7      .1       0
Bank Sta=703.2,750.7
XS Rating Curve= 0 ,0
Exp/Cntr=0.3,0.1

Type RM Length L Ch R = 1 ,4693.5  ,395.7,382.4,373.6
XS GIS Cut Line= 3
     1864716.819      648749.832     1865207.271       648877.87
     1865725.934      648999.398
#Sta/Elev= 30
       0  838.96   107.2  816.95   165.7  806.38   185.2  804.37   224.2  803.69
   243.7  800.84   263.2   796.2   311.9  779.87   331.4  774.74   341.2  772.89
   360.7  771.29   389.9   770.1   399.7  768.73   409.4  765.34   419.2  760.54
   467.9  736.31   487.4   725.6   497.1  722.54   506.9     722   516.6  722.13
   526.3  723.08     536  725.17   632.8  746.06     720  766.12   778.1   783.8
   884.6  813.31   894.3  817.07   923.4  830.01   952.4  840.23  1039.6  863.57
#Mann= 3 , 0 , 0
       0     .08       0   487.4    .045       0     536      .1       0
Bank Sta=487.4,536
XS Rating Curve= 0 ,0
Exp/Cntr=0.3,0.1

Type RM Length L Ch R = 1 ,4311.1  ,403.2,400,390.9
XS GIS Cut Line= 3
      1864768.29      649396.373     1865196.534       649248.16
     1865652.584      649155.391
#Sta/Elev= 30
       0  823.81    19.3  822.67    57.8   822.3    77.1  821.37    96.4  819.31
   115.7  815.52   192.8  795.72   279.6  772.15   347.1   756.1   356.8  753.04
     405  735.92   433.9  724.94   443.5  722.62   453.2     722   462.9  722.06
   472.6  722.85   482.2  724.72     492   726.6   540.4  733.46   550.1  735.55
   559.8   738.5     618  759.14   627.7  762.26   637.4  764.39   705.2   772.9
   850.7  801.96   860.4  804.39   870.1  807.73   899.2  820.04   918.6  827.51
#Mann= 3 , 0 , 0
       0      .1       0   433.9    .045       0   482.2     .08       0
Bank Sta=433.9,482.2
XS Rating Curve= 0 ,0
Exp/Cntr=0.3,0.1

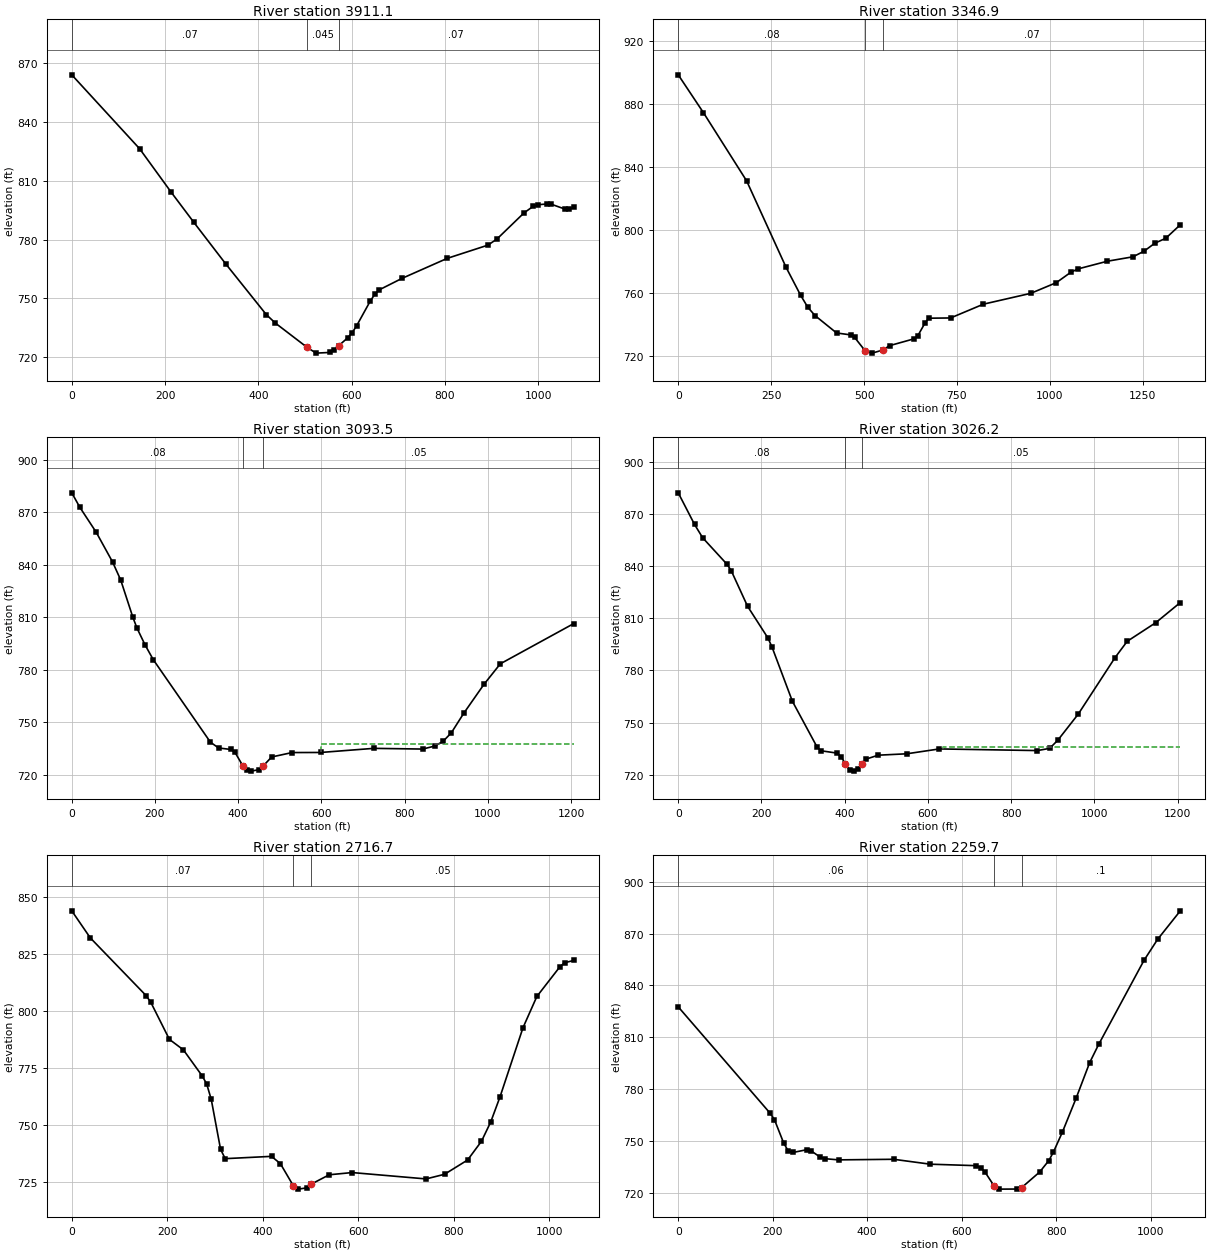
Type RM Length L Ch R = 1 ,3911.1  ,577.5,564.2,552.7
XS GIS Cut Line= 3
     1864762.392      649884.815     1865257.002      649637.801
     1865708.429      649372.125
#Sta/Elev= 30
       0  864.18   145.5  826.42   213.4  804.14   261.9  788.77   329.8   767.7
   417.1   741.7   436.5  737.37   504.4  724.99   523.8     722   552.9  722.34
   562.6   723.7   572.3  725.76   591.7  729.83   601.4  732.47   611.1  736.07
   640.2  748.63   649.9  752.08   659.6  754.36   708.1  760.18   805.1  770.41
   892.4  777.17   911.8  780.29     970  793.68   989.4  796.97   999.1  797.81
  1018.5  798.18  1028.2  798.08  1057.3  795.62    1067  795.43  1076.7   796.5
#Mann= 3 , 0 , 0
       0     .07       0   504.4    .045       0   572.3     .07       0
Bank Sta=504.4,572.3
XS Rating Curve= 0 ,0
Exp/Cntr=0.3,0.1

Type RM Length L Ch R = 1 ,3346.9  ,264.7,253.4,242.6
XS GIS Cut Line= 4
      1865033.66      650607.471     1865317.948      650227.697
     1865398.243      650088.808     1865737.586      649458.113
#Sta/Elev= 30
       0  898.28    67.8  874.31     184  831.13   290.4  776.24   329.2   758.7
   348.5  751.11   367.9  745.82     426  734.78   464.7  733.53   474.4  732.01
   502.7  723.55   521.6     722   549.9  723.91   568.8  726.74   634.8  731.08
   644.6  732.98   664.2  741.16   674.1  744.12   732.9  744.28   821.2  753.01
   948.8  759.89  1017.4  766.65  1056.7  773.27  1076.3  775.38  1154.8  780.22
  1223.5  783.01  1252.9  786.49  1282.3  791.61  1311.8  794.74    1351  803.31
#Mann= 3 , 0 , 0
       0     .08       0   502.7    .045       0   549.9     .07       0
Bank Sta=502.7,549.9
XS Rating Curve= 0 ,0
Exp/Cntr=0.3,0.1

Type RM Length L Ch R = 1 ,3093.5  ,67.3,67.3,67.3
XS GIS Cut Line= 4
      1865597.45      650657.267     1865587.675      650255.642
     1865588.117      650167.289     1865762.826      649472.489
#Sta/Elev= 30
       0  881.16    19.6   872.8    58.8  858.58      98  841.64   117.6  831.29
     147  809.86   156.8  803.74   176.4  794.06     196  785.69   333.2  738.55
   352.8  735.25   382.2  734.39     392  732.82   411.6  724.83   421.4  722.48
   431.2     722   450.8  722.88   460.6  725.12   480.3  730.09   529.4  732.62
     598  732.67   725.6  735.02   843.4  734.62   872.8  736.38   892.5   739.1
   912.1  743.91   941.6  754.97   990.6  771.66  1029.9  783.39  1206.5  806.41
#Mann= 3 , 0 , 0
       0     .08       0   411.6    .045       0   460.6     .05       0
#XS Ineff= 2 , 0
                          600.09          737.47
Permanent Ineff=
       F       F
Bank Sta=411.6,460.6
XS Rating Curve= 0 ,0
Exp/Cntr=0.3,0.1

Type RM Length L Ch R = 1 ,3026.2  ,317.8,309.6,301.3
XS GIS Cut Line= 4
     1865664.724      650642.076     1865654.949      650240.451
     1865655.391      650152.098     1865830.101      649457.298
#Sta/Elev= 30
       0   882.1    39.2  863.91    58.8  856.25   117.6  840.93   127.4  837.32
   166.6   816.9   215.6  798.65   225.4  793.44   274.4  762.26   333.2   736.2
     343  733.86   382.2   732.5     392  730.23   401.7  726.26   411.6  722.96
   421.4  722.16   431.2  723.35     441   726.3   450.8  729.01   480.3  731.32
     549  732.12   627.5  734.92     863  733.97   892.5  735.24   912.1  739.92
   961.2  754.92  1049.5  787.35  1078.9  796.77  1147.6  807.49  1206.5  819.05
#Mann= 3 , 0 , 0
       0     .08       0   401.7    .045       0     441     .05       0
#XS Ineff= 2 , 0
                          636.31          736.03
Permanent Ineff=
       F       F
Bank Sta=401.7,441
XS Rating Curve= 0 ,0
Exp/Cntr=0.3,0.1

Type RM Length L Ch R = 1 ,2716.7  ,444.2,457,469.8
XS GIS Cut Line= 4
     1866073.514      650507.881     1865934.267       650123.53
     1865884.354      649993.322     1865895.249      649490.711
#Sta/Elev= 30
       0  843.98    38.9   832.1   155.7  806.82   165.5  803.87   204.4  787.65
   233.6  783.08   272.5   771.8   282.3  768.21     292  761.33   311.5  739.48
   321.2   735.4   418.1  736.41   436.7  733.21   463.5  723.63   473.9  722.05
   492.5  722.62   501.8   724.3     539  728.34   586.9  729.31   741.6  726.52
   780.3  728.55   828.6  734.81   857.6  743.01     877  751.47   896.3  762.39
   944.6   792.8   973.6  806.46    1022  819.52  1031.6  821.24    1051  822.25
#Mann= 3 , 0 , 0
       0     .07       0   463.5    .045       0   501.8     .05       0
Bank Sta=463.5,501.8
XS Rating Curve= 0 ,0
Exp/Cntr=0.3,0.1

Type RM Length L Ch R = 1 ,2259.7  ,361.7,374.4,387.1
XS GIS Cut Line= 4
     1866169.156      650486.912      1866263.47      649883.301
     1866291.906      649741.586     1866347.462      649439.502
#Sta/Elev= 30
       0   827.6     194  766.12   203.6  762.26     223  748.81   232.7  744.13
   242.4  743.22   271.5  744.81   281.2  744.18   300.6   740.5   310.3  739.64
   339.4  738.95   455.8  739.29   533.4  736.45   630.2  735.59   639.8  734.47
   649.5  731.78   668.8  723.73   678.4     722   716.9  722.05   726.6  722.83
   765.1  731.96   784.3  738.54   793.9  743.39   813.1  755.08   841.9  774.56
   870.7  795.25   889.8  805.83   985.8  854.56  1014.6  866.73  1062.6  883.23
#Mann= 3 , 0 , 0
       0     .06       0   668.8    .045       0   726.6      .1       0
Bank Sta=668.8,726.6
XS Rating Curve= 0 ,0
Exp/Cntr=0.3,0.1

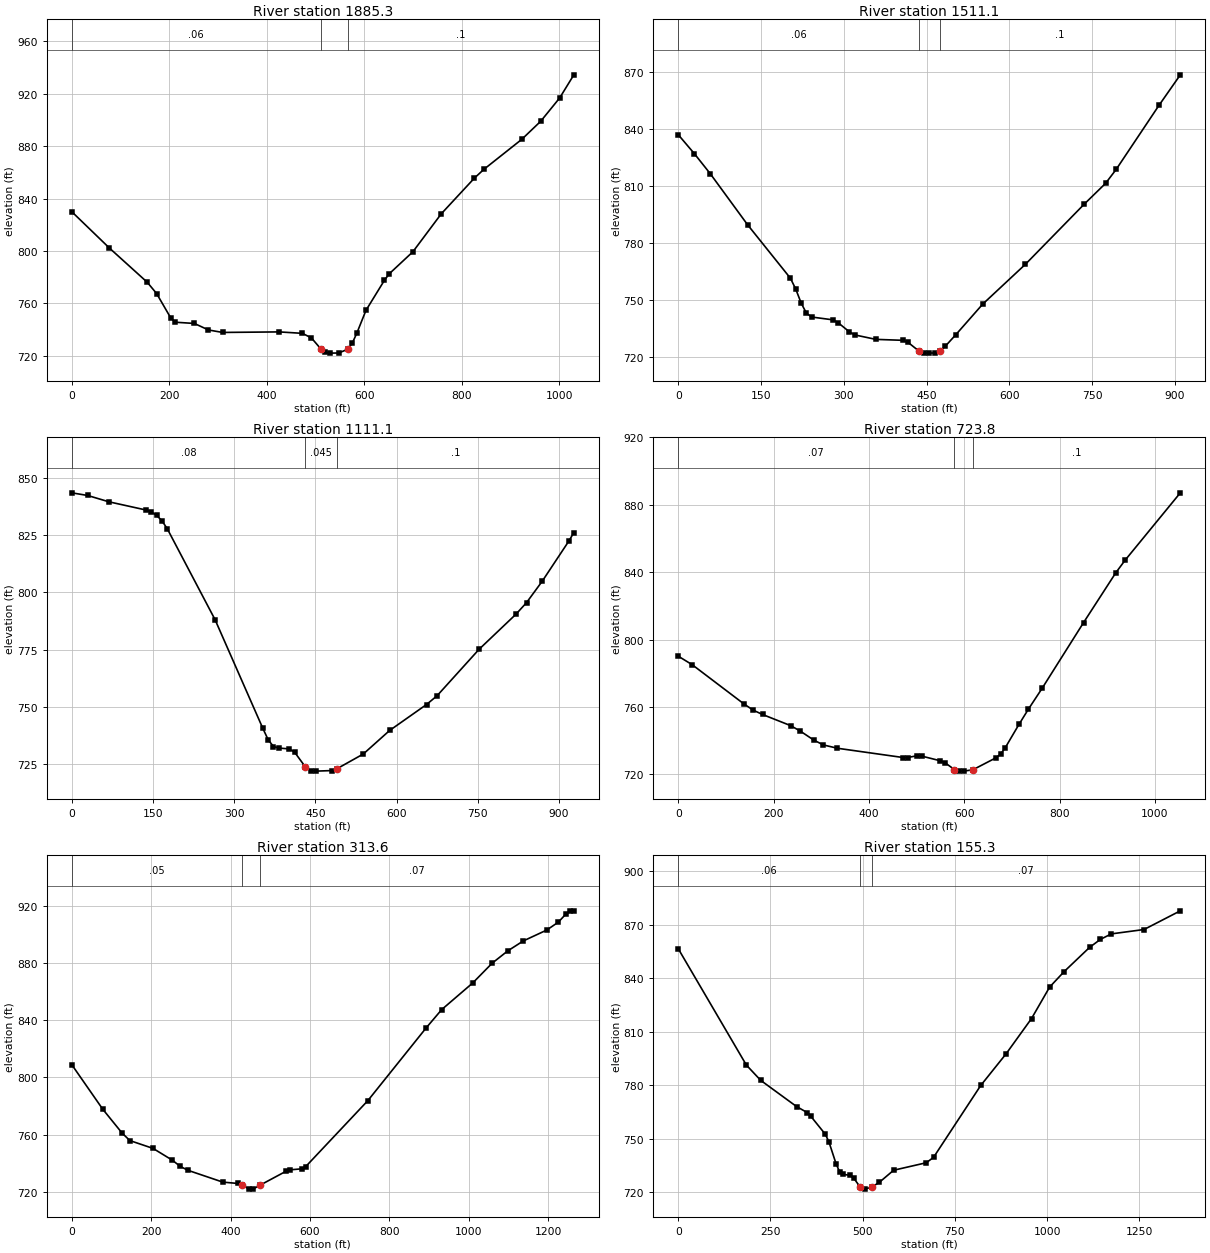
Type RM Length L Ch R = 1 ,1885.3  ,367.5,374.2,380.8
XS GIS Cut Line= 4
     1866251.211      650534.294     1866472.462      650137.419
     1866589.461      650017.387     1866896.073       649748.53
#Sta/Elev= 30
       0  830.01    77.3  802.22   154.7  776.16     174  767.51     203  748.89
   212.7  745.59   251.4  744.67   280.4  739.68   309.4   737.8   425.4  738.21
     473  737.11   491.6   733.6   510.2  725.51   519.6  722.67   528.9     722
   547.5   722.1   566.1  724.99   575.4   729.7   584.8  737.35   603.4  754.65
   641.4  777.69   651.1  782.56   699.7  799.42   757.9  828.41   825.9  855.69
   845.3  862.36     923  885.27   961.8  899.06  1000.7  916.87  1029.8  934.54
#Mann= 3 , 0 , 0
       0     .06       0   510.2    .045       0   566.1      .1       0
Bank Sta=510.2,566.1
XS Rating Curve= 0 ,0
Exp/Cntr=0.3,0.1

Type RM Length L Ch R = 1 ,1511.1  ,396.4,400,402.1
XS GIS Cut Line= 3
      1866320.56      650628.113     1866715.223      650401.694
     1867109.886      650175.274
#Sta/Elev= 30
       0  837.18      29  827.25    58.1  816.58   125.8  789.64   203.3   761.5
     213  755.76   222.7  748.47   232.3  743.05     242  741.03   280.7  739.54
   290.4  737.89   309.8  733.33   319.5  731.63   358.2  729.25   406.6  728.76
   416.3  727.72   435.6  723.25   445.3   722.1     455     722   464.7  722.09
   474.4  723.04     484  725.62   503.4  731.81   551.8  747.82   629.3  768.86
   735.7  800.51   774.5  811.51   793.8  818.89   871.3  852.63     910  868.74
#Mann= 3 , 0 , 0
       0     .06       0   435.6    .045       0   474.4      .1       0
Bank Sta=435.6,474.4
XS Rating Curve= 0 ,0
Exp/Cntr=0.3,0.1

Type RM Length L Ch R = 1 ,1111.1  ,384.4,387.2,391.5
XS GIS Cut Line= 3
     1866418.452      650933.712     1866840.519      650774.857
     1867274.044      650577.686
#Sta/Elev= 30
       0  843.51    29.4  842.35    68.6  839.59   137.2     836   147.1  835.17
   156.9  833.62   166.7  831.26   176.5  827.76   264.7  788.09   352.9  740.64
   362.7   735.7   372.5  732.74   382.4  732.08     402  731.69   411.8  730.17
   431.4  723.84   441.2  722.24     451     722   480.1  722.24   489.8  723.05
   538.4  729.48     587  739.75   655.1  751.08   674.5  754.88   752.3  775.22
   820.3  790.51   839.8  795.56   868.9  804.95   917.5  822.28   927.2  826.14
#Mann= 3 , 0 , 0
       0     .08       0   431.4    .045       0   489.8      .1       0
Bank Sta=431.4,489.8
XS Rating Curve= 0 ,0
Exp/Cntr=0.3,0.1

Type RM Length L Ch R = 1 ,723.8   ,407.4,410.2,413.1
XS GIS Cut Line= 4
     1866409.094      651082.732     1866957.705      651122.662
     1867061.445      651097.477     1867447.288      651006.343
#Sta/Elev= 30
       0  790.22    29.5  785.11   137.5  761.94   157.2  758.19   176.8  755.62
   235.7  749.01   255.4  745.87   284.8  740.35   304.5  737.54     334  735.57
   471.5  730.08   481.3  730.08     501  731.11   510.8  730.92   550.1  728.12
   559.8  726.97   579.2  722.96   588.9  722.05   598.6     722     618  722.78
   666.5   729.9   676.2  732.08   685.8  735.77   714.8  749.72   734.2  758.59
   763.2  771.06   850.2  810.09   917.9  839.69   937.2  847.07  1053.3  887.15
#Mann= 3 , 0 , 0
       0     .07       0   579.2    .045       0     618      .1       0
Bank Sta=579.2,618
XS Rating Curve= 0 ,0
Exp/Cntr=0.3,0.1

Type RM Length L Ch R = 1 ,313.6   ,171.7,158.3,144.9
XS GIS Cut Line= 4
     1866523.944      651535.395     1866932.965      651512.419
     1867062.628      651497.718     1867748.938      651265.023
#Sta/Elev= 30
       0  808.95      78  777.82   126.8  761.11   146.3  755.87   204.8  750.38
   253.6   742.1   273.1  737.84   292.6  735.08   380.4  726.82     419  725.86
   428.3  724.78     447  721.91   456.3  721.92   474.9  724.76   540.2  734.48
     550  735.41   579.3   736.1   589.1   737.6   745.8  783.78   892.7  834.65
   931.9  847.47  1010.2  866.12  1059.2  879.97  1098.4  888.54  1137.5  895.49
  1196.3  903.06  1225.7  908.62  1245.3  914.46    1255  916.13  1264.8  916.54
#Mann= 3 , 0 , 0
       0     .05       0   428.3    .045       0   474.9     .07       0
Bank Sta=428.3,474.9
XS Rating Curve= 0 ,0
Exp/Cntr=0.3,0.1

Type RM Length L Ch R = 1 ,155.3   ,68.1,68.1,68.1
XS GIS Cut Line= 4
     1866590.083      651911.725      1866971.16      651696.881
     1867075.326      651608.339     1867814.042      651336.638
#Sta/Elev= 30
       0   856.5   184.7  791.26   223.6  782.68   320.8     768     350  764.58
   359.7  762.48   398.6   752.5   408.3  748.34   427.8  735.99   437.5  731.38
   447.2  729.97   466.8  729.39   476.5  727.67   492.2  723.15   505.8  721.68
   525.4   722.9   544.9  725.44     584  732.27   672.6  736.48   692.2  739.49
   820.2  779.82     889  797.58   957.9  817.35  1007.1  835.02  1046.4  843.69
  1115.3  857.25  1144.8  861.76  1174.3  864.82  1262.9  867.27  1361.3  877.75
#Mann= 3 , 0 , 0
       0     .06       0   492.2    .045       0   525.4     .07       0
Bank Sta=492.2,525.4
XS Rating Curve= 0 ,0
Exp/Cntr=0.3,0.1

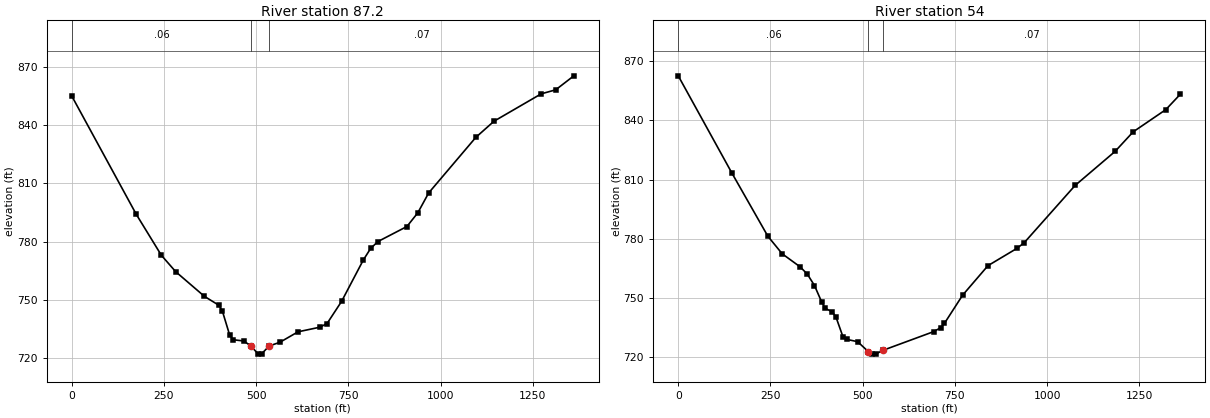
Type RM Length L Ch R = 1 ,87.2    ,33.2,33.2,33.2
XS GIS Cut Line= 4
     1866623.938       651971.62     1867005.014      651756.777
     1867109.181      651668.235     1867847.896      651396.534
#Sta/Elev= 30
       0  855.02     175  794.01     243  772.93   281.9  764.48   359.7  751.78
   398.6  747.23   408.3  744.23   427.8  732.04   437.5  729.43   466.8  728.79
   486.3  726.06   505.8  722.02   515.6  722.33   535.1   726.2   564.4  728.14
   613.5  733.52   672.6  735.89   692.2  737.79   731.6  749.21   790.6  770.57
   810.3  776.46     830  780.02   908.7  787.78   938.2  794.83   967.7  805.08
  1095.6  833.72  1144.8  842.03  1272.7  856.13  1312.1  858.21  1361.3  865.42
#Mann= 3 , 0 , 0
       0     .06       0   486.3    .045       0   535.1     .07       0
Bank Sta=486.3,535.1
XS Rating Curve= 0 ,0
Exp/Cntr=0.3,0.1

Type RM Length L Ch R = 1 ,54      ,54.7,54,53.4
XS GIS Cut Line= 4
     1866623.938      652015.023     1867005.014       651800.18
     1867109.181      651711.638     1867847.896      651439.936
#Sta/Elev= 30
       0   862.5   145.8  813.18     243  781.31   281.9  772.41   330.5  765.81
     350  762.13   369.4  756.36   388.9  748.03   398.6  744.82     418  742.96
   427.8  740.33   447.2  730.11     457  729.08   486.3  727.94   515.6  722.87
   525.4  721.64   535.1  721.63   554.6  723.53   692.2  732.99   711.9  735.03
   721.8  737.21     771  751.46   839.8  766.41   918.5  775.18   938.2  778.06
    1076     807  1184.2   824.2  1233.4  834.13  1321.9  845.38  1361.3  853.17
#Mann= 3 , 0 , 0
       0     .06       0   515.6    .045       0   554.6     .07       0
Bank Sta=515.6,554.6
XS Rating Curve= 0 ,0
Exp/Cntr=0.3,0.1

Chan Stop Cuts=-1
Use User Specified Reach Order=0
Composite Channel Slope=5